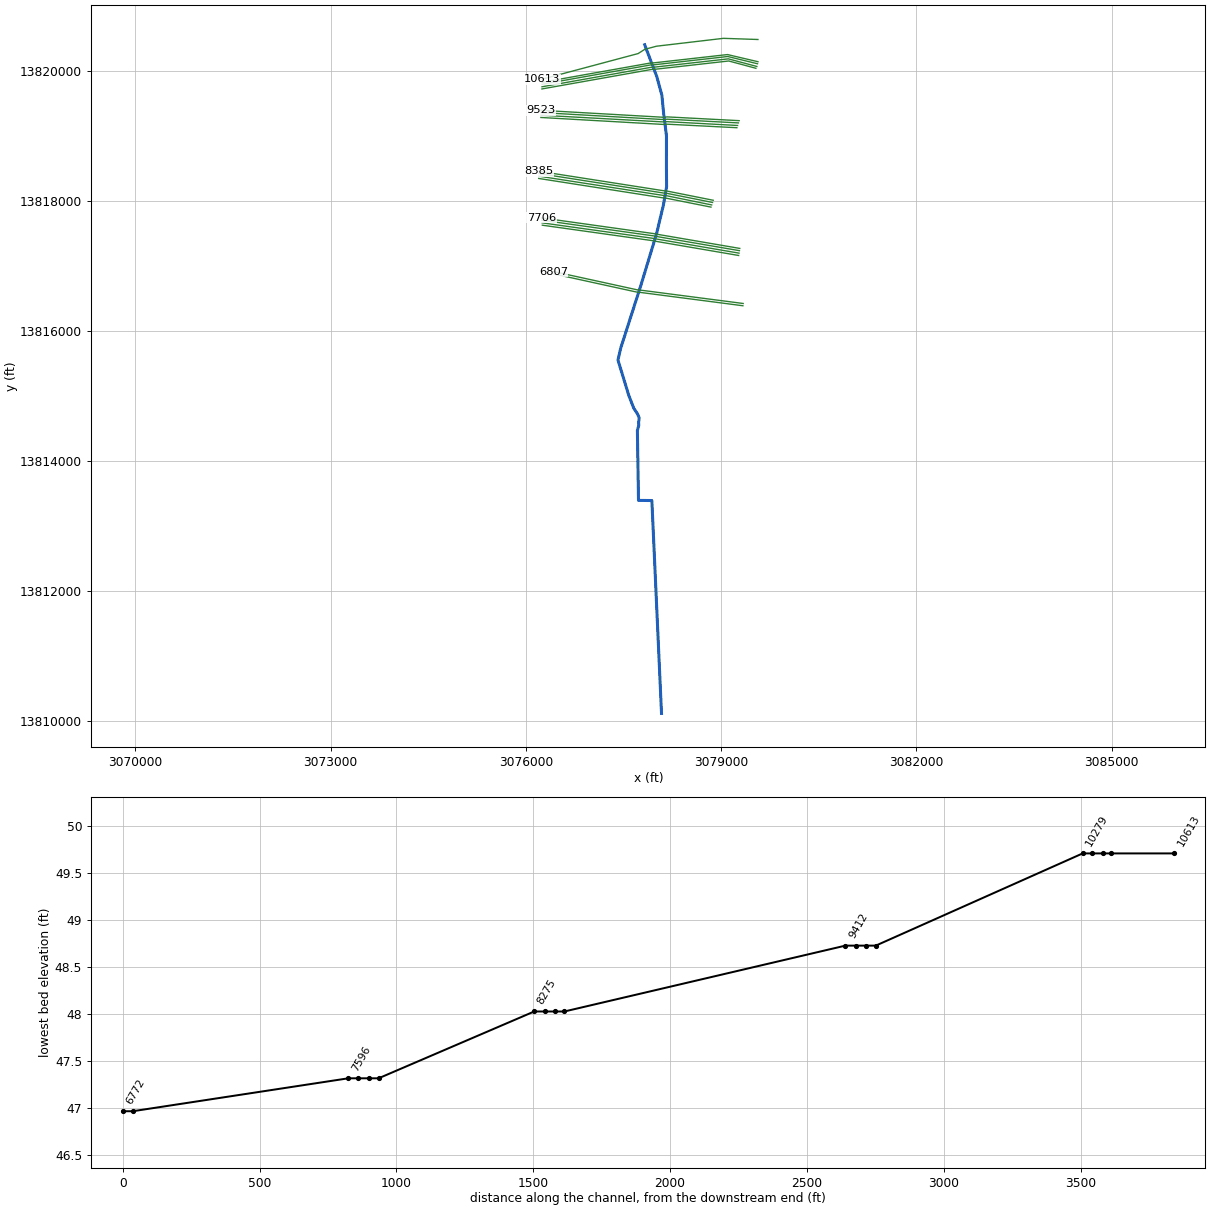
--- D133-00-00.prj (project) ---

Proj Title=D133-00-00
Current Plan=p02
Default Exp/Contr=.3,.1
English Units
Geom File=g01
Flow File=f01
Flow File=f06
Plan File=p01
Plan File=p02
Y Axis Title=Elevation
X Axis Title(PF)=Main Channel Distance
X Axis Title(XS)=Station
BEGIN DESCRIPTION:
Brays Bayou Watershed
Tributary 17.42
HCFCD Unit D133-00-00
Flood Hazard & Floodway Model
10, 2, 1, 0.2% Event
Filename D133.prj
Prepared by: Dodson & Associates, Inc.   Date: September 2003
Reviewed by:____________________	 Date:_________
STATUS (Final RAS)
FOR FLOOD HARZARD RECOVERY DATA ONLY,03/02/2004
Will Be Voided Upon Release of The Preliminary DFIRM
END DESCRIPTION:
DSS File=dss
DSS Export Rating Curves= 0
DSS Export Rating Curve Sorted= 0
DSS Export Volume Flow Curves= 0
DXF OffsetX= 0
DXF OffsetY= 0
DXF ScaleX= 1
DXF ScaleY= 10

--- D133-00-00.p02 (plan) ---

Plan Title=Floodway
Version=Version 3.0.1  Mar 2001
Short Identifier=Floodway0607
Geom File=g01
Flow File=f06
Subcritical Flow
K Sum by GR= 0
Std Step Tol= 0.01
Critical Tol= 0.01
Num of Std Step Trials= 20
Max Error Tol= 0.3
Flow Tol Ratio= 0.001
Split Flow NTrial= 30
Split Flow Tol= 0.02
Split Flow Ratio= 0.02
Log Output Level= 0
Friction Slope Method= 2
Unsteady Friction Slope Method= 2
Secant Critical Depth
Global Vel Dist= 0 , 0 , 0
Global Log Level= 0
CheckData=True
Encroach Param=-1 ,0,0, 2
Encroach River=D133-00-00
Encroach Reach=Reach 0
Encroach Node=10613
       1 1708.05 1746.27
Encroach Node=10384
       1 1637.55 1675.77
Encroach Node=10352
       1 1600.55 1661.77
Encroach Node=10332
       1 1600.55 1661.77
Encroach Node=10314
       1 1600.55 1661.77
Encroach Node=10279
       1 1576.55 1614.77
Encroach Node=9523
       1 1126.65 1164.84
Encroach Node=9488
       1 1091.65 1147.84
Encroach Node=9469
       1 1091.65 1147.84
Encroach Node=9451
       1 1091.65 1147.84
Encroach Node=9412
       1 1075.65 1113.84
Encroach Node=8385
       1  726.79  765.35
Encroach Node=8350
       1  712.79  759.35
Encroach Node=8331
       1  712.79  759.35
Encroach Node=8313
       1  712.79  759.35
Encroach Node=8275
       1  706.79  745.35
Encroach Node=7706
       1    1200    1340
Encroach Node=7671
       1    1180    1349
Encroach Node=7651
       1    1170    1349
Encroach Node=7632
       1    1150    1349
Encroach Node=7596
       1    1130    1347
Encroach Node=6807
       1    1579    1646
Encroach Node=6772
       1    1580    1663
Encroach Node=6747
       1    1580    1663
Encroach Node=6716
       1 1590.72    1649
Encroach Node=6695
       1 1602.72 1652.22
Encroach Node=5893
       1 1862.42 1909.43
Encroach Node=5859
       1 1883.42 1930.43
Encroach Node=5759
       1 1883.42 1992.43
Encroach Node=5730
       1 1945.42 1992.43
Encroach Node=5709
       1 1959.42 2006.43
Encroach Node=5326
       1 1525.79 1595.63
Encroach Node=4548
       1  478.15  550.77
Encroach Node=4485
       1  489.18  548.42
Encroach Node=4424
       1  485.18  548.42
Encroach Node=4377
       1  485.18  544.42
Encroach Node=4303
       1  493.18  552.42
Encroach Node=3187
       1  295.45  351.09
Encroach Node=3152
       1  297.45  348.92
Encroach Node=3144
       1  296.95  348.92
Encroach Node=3138
       1  296.95  348.42
Encroach Node=3115
       1  295.45  351.09
Encroach Node=1888
       1  275.86  326.29
Encroach Node=1847
       1  282.98  322.84
Encroach Node=1845
       1  282.98  323.84
Encroach Node=1839
       1  283.98  323.84
Encroach Node=1804
       1  279.86  330.29
Encroach Node=611
       1  373.08  411.34
Encroach Reach=D133-00-00_0006
Encroach Node=10613
       1 1708.05 1746.27
Encroach Node=10384
       1 1637.55 1675.77
Encroach Node=10352
       1 1600.55 1661.77
Encroach Node=10332
       1 1600.55 1661.77
Encroach Node=10314
       1 1600.55 1661.77
Encroach Node=10279
       1 1576.55 1614.77
Encroach Node=9523
       1 1126.65 1164.84
Encroach Node=9488
       1 1091.65 1147.84
Encroach Node=9469
       1 1091.65 1147.84
Encroach Node=9451
       1 1091.65 1147.84
Encroach Node=9412
       1 1075.65 1113.84
Encroach Node=8385
       1  726.79  765.35
Encroach Node=8350
       1  712.79  759.35
Encroach Node=8331
       1  712.79  759.35
Encroach Node=8313
       1  712.79  759.35
Encroach Node=8275
       1  706.79  745.35
Encroach Node=7706
       1    1200    1340
Encroach Node=7671
       1    1180    1349
Encroach Node=7651
       1    1170    1349
Encroach Node=7632
       1    1150    1349
Encroach Node=7596
       1    1130    1347
Encroach Node=6807
       1    1579    1646
Encroach Node=6772
       1    1580    1663
Encroach Node=6747
       1    1580    1663
Encroach Node=6716
       1 1590.72    1649
Encroach Node=6695
       1 1602.72 1652.22
Encroach Node=5893
       1 1862.42 1909.43
Encroach Node=5859
       1 1883.42 1930.43
Encroach Node=5759
       1 1883.42 1992.43
Encroach Node=5730
       1 1945.42 1992.43
Encroach Node=5709
       1 1959.42 2006.43
Encroach Node=5326
       1 1525.79 1595.63
Encroach Node=4548
       1  478.15  550.77
Encroach Node=4485
       1  489.18  548.42
Encroach Node=4424
       1  485.18  548.42
Encroach Node=4377
       1  485.18  544.42
Encroach Node=4303
       1  493.18  552.42
Encroach Node=3187
       1  295.45  351.09
Encroach Node=3152
       1  297.45  348.92
Encroach Node=3144
       1  296.95  348.92
Encroach Node=3138
       1  296.95  348.42
Encroach Node=3115
       1  295.45  351.09
Encroach Node=1888
       1  275.86  326.29
Encroach Node=1847
       1  282.98  322.84
Encroach Node=1845
       1  282.98  323.84
Encroach Node=1839
       1  283.98  323.84
Encroach Node=1804
       1  279.86  330.29
Encroach Node=611
       1  373.08  411.34
Computation Interval=1HOUR
Output Interval=1HOUR
Run HTab= 0
Run UNet= 0
Run PostProcess= 0
UNET Theta= 1
UNET ZTol= 0.02
UNET ZSATol= 0.1
UNET MxIter= 20
UNET MaxInSteps= 20
UNET DtIC= 0
UNET DtMin= 0
UNET MaxCRTS= 20
UNET WFStab= 2
UNET SFStab= 1
UNET WFX= 1
UNET SFX= 1
UNET Convert EG Bridges=-1
UNET Use Existing IB Tables=-1
Instantaneous Interval=1HOUR
DSS File=dss
Write IC File= 0
Write Velocity= 0
Write Detailed= 0

--- D133-00-00.p01 (plan) ---

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Plan Title=FEMA Effective June 2007
Short Identifier=FEMAeff0607
Geom File=g01
Flow File=f01
Encroach Param=-1 ,0,0, 0

--- D133-00-00.f06 (steady flow) ---

Flow Title=Floodway
Version=Version 3.0.1  Mar 2001
Number of Profiles= 2
Profile Names=1PCT_100yr,1PCTFloodway_100yrFW
River Rch & RM=D133-00-00,D133-00-00_0006 ,10613
    1788    1788
River Rch & RM=D133-00-00,D133-00-00_0006 ,8275
    1830    1830
River Rch & RM=D133-00-00,D133-00-00_0006 ,6695
    1868    1868
River Rch & RM=D133-00-00,D133-00-00_0006 ,5326
    1930    1930
River Rch & RM=D133-00-00,D133-00-00_0006 ,3115
    2021    2021
Boundary for River Rch & Prof#=D133-00-00,D133-00-00_0006 , 1
Up Type= 0
Dn Type= 1
Dn Known WS=54.18
Boundary for River Rch & Prof#=D133-00-00,D133-00-00_0006 , 2
Up Type= 0
Dn Type= 1
Dn Known WS=54.18
DSS Import GetInterval= 0
DSS Import GetPeak= 0
DSS Import FillOption= 0

--- D133-00-00.f01 (steady flow) ---

Flow Title=FEMA Effective June 2007
Version=Version 3.0.1  Mar 2001
Number of Profiles= 4
Profile Names=10PCT_10yr,2PCT_50yr,1PCT_100yr,0.2PCT_500yr
River Rch & RM=D133-00-00,D133-00-00_0006 ,10613
    1048    1537    1788    2504
River Rch & RM=D133-00-00,D133-00-00_0006 ,8275
    1064    1570    1830    2580
River Rch & RM=D133-00-00,D133-00-00_0006 ,6695
    1077    1599    1868    2647
River Rch & RM=D133-00-00,D133-00-00_0006 ,5326
    1100    1648    1930    2759
River Rch & RM=D133-00-00,D133-00-00_0006 ,3115
    1133    1719    2021    2925
Boundary for River Rch & Prof#=D133-00-00,D133-00-00_0006 , 1
Up Type= 0
Dn Type= 3
Dn Slope=.001
Boundary for River Rch & Prof#=D133-00-00,D133-00-00_0006 , 2
Up Type= 0
Dn Type= 3
Dn Slope=.001
Boundary for River Rch & Prof#=D133-00-00,D133-00-00_0006 , 3
Up Type= 0
Dn Type= 3
Dn Slope=.001
Boundary for River Rch & Prof#=D133-00-00,D133-00-00_0006 , 4
Up Type= 0
Dn Type= 3
Dn Slope=.001
DSS Import GetInterval= 0
DSS Import GetPeak= 0
DSS Import FillOption= 0

--- D133-00-00.g01 (geometry) ---

Geom Title=D133-00-00 June 2007
Version=Version 3.0.1  Mar 2001

River Reach=D133-00-00      ,D133-00-00_0006
Reach XY= 30
     3077826.831    13820398.598     3078011.745    13819914.258
     3078090.862     13819623.59     3078118.162    13819343.062
     3078161.549    13818999.289     3078161.033    13818512.282
     3078163.413    13818217.654     3078113.974    13817933.166
     3078008.503    13817492.005     3077767.363    13816697.832
     3077458.059    13815733.544     3077416.134    13815551.968
     3077477.843    13815350.108      3077584.68    13815000.883
     3077658.519    13814812.464     3077714.293    13814725.635
      3077743.17    13814663.049     3077733.677    13814598.483
     3077736.315    13814547.358     3077714.693    13814469.351
     3077731.716    13813393.749     3077937.008    13813391.526
      3078037.13     13811182.13     3078041.681    13811081.681
     3078048.835    13810923.835     3078060.539    13810665.539
     3078067.693    13810507.693     3078072.244    13810407.244
     3078079.398    13810249.398     3078085.306    13810119.004

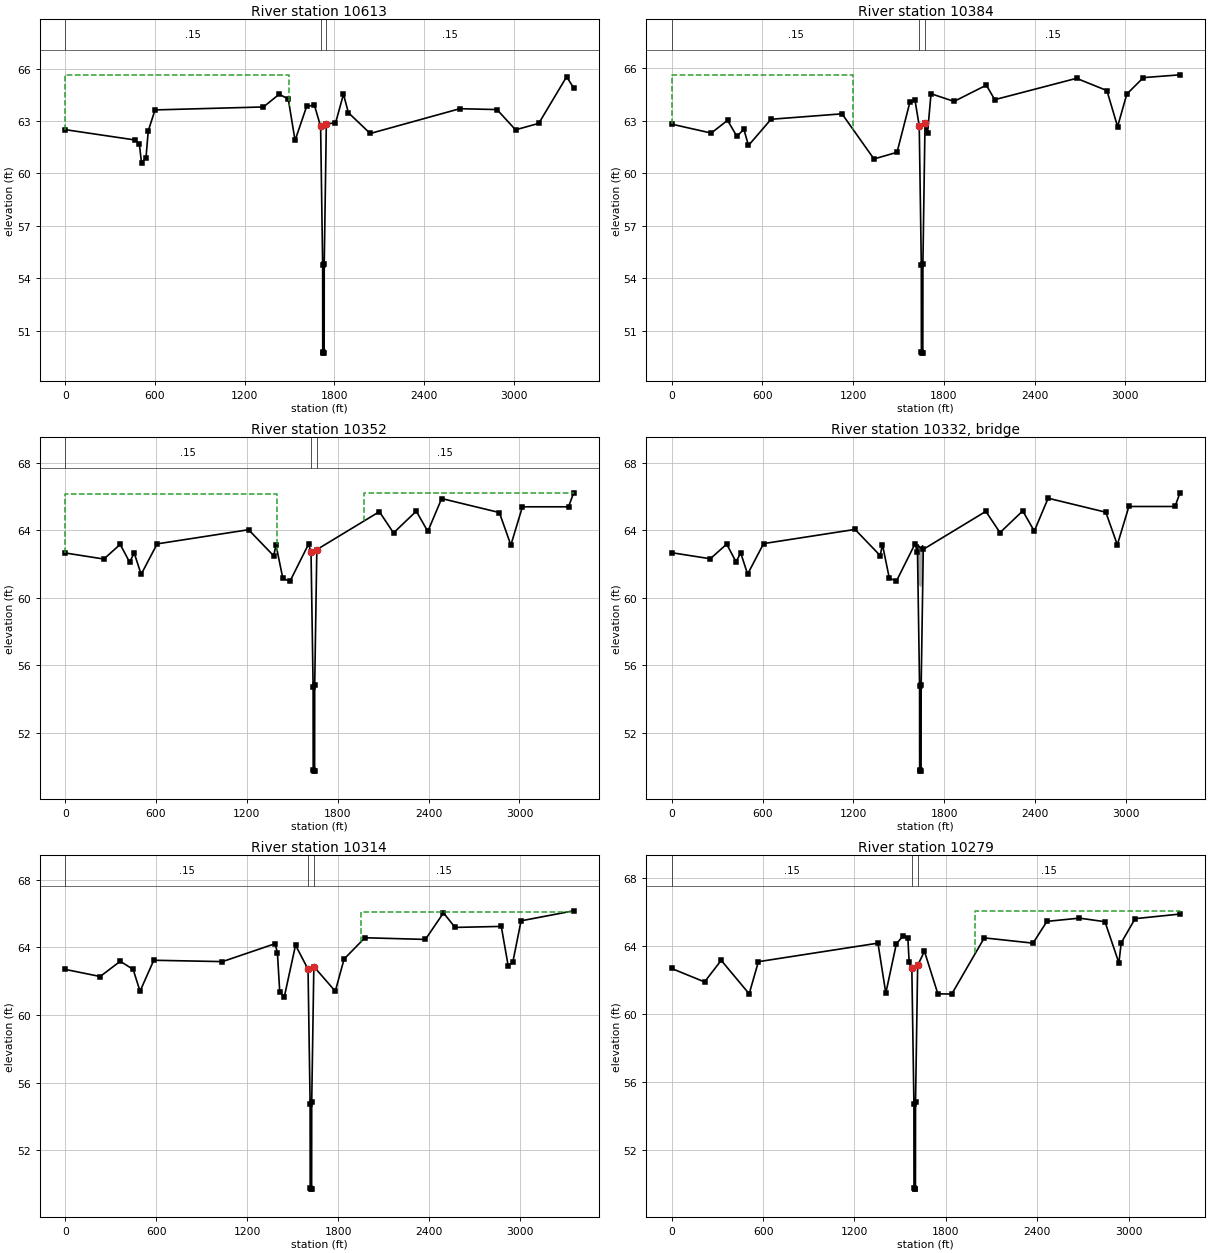
Type RM Length L Ch R = 1 ,10613   ,282.45,228.85,176.04
BEGIN DESCRIPTION:
              10636.6
END DESCRIPTION:
XS GIS Cut Line= 6
     3079567.424    13820480.435     3079036.554    13820498.256
     3078009.469     13820377.42     3077829.184    13820329.981
     3077726.145     13820264.09     3076252.865    13819870.369
#Sta/Elev= 30
       0   62.51  465.19   61.92  495.64   61.71  510.21    60.6  540.29   60.91
  555.39   62.44   600.7   63.64 1325.67   63.81 1431.39   64.54  1491.8   64.26
 1537.11   61.89 1614.53   63.84 1666.03   63.92 1708.05    62.7 1721.75   54.73
 1722.21   49.75 1727.05   49.71 1731.72   49.72 1732.31   54.83 1746.27   62.86
 1807.57   62.88 1860.98   64.54 1893.76   63.48 2039.81   62.29 2639.03   63.71
 2887.67   63.66 3011.66    62.5 3166.93   62.87 3353.24   65.54 3399.44   64.91
#Mann= 3 , 0 , 0
       0     .15       0 1708.05    .015       0 1746.27     .15       0
#XS Ineff= 2 , 0
       0 1498.96   65.65 1895.55       0
Permanent Ineff=
       T       T
Bank Sta=1708.05,1746.27
XS Rating Curve= 0
Exp/Cntr=.3,.1

Type RM Length L Ch R = 1 ,10384   ,33.8,31.41,30.03
BEGIN DESCRIPTION:
             10407.75
END DESCRIPTION:
XS GIS Cut Line= 5
     3079567.424    13820138.756     3079098.939    13820248.649
     3077975.305    13820122.315     3077911.944     13820118.59
     3076251.166    13819822.321
#Sta/Elev= 30
       0    62.8  261.84   62.29  369.69   63.02  431.32    62.1  477.54   62.51
  507.81   61.58  657.27   63.08 1126.68   63.39 1338.01   60.81 1490.59   61.19
 1575.62   64.05 1609.71   64.16 1637.55    62.7 1651.25   54.73 1651.71   49.75
 1656.55   49.71 1661.22   49.72 1661.81   54.83 1675.77   62.86 1692.26   62.27
 1715.45   64.54 1867.82    64.1 2081.34   65.03 2136.98    64.2 2678.07   65.42
 2878.78   64.72 2949.63   62.66 3010.58   64.52 3119.87   65.46 3362.38   65.62
#Mann= 3 , 0 , 0
       0     .15       0 1637.55    .015       0 1675.77     .15       0
#XS Ineff= 2 , 0
       0 1200.62   65.61 1847.26       0
Permanent Ineff=
       T       T
Bank Sta=1637.55,1675.77
XS Rating Curve= 0
Exp/Cntr=.5,.3

Type RM Length L Ch R = 1 ,10352   ,41.4,38.22,37.13
BEGIN DESCRIPTION:
             10376.34
END DESCRIPTION:
XS GIS Cut Line= 5
     3079560.447    13820107.377     3079102.893    13820218.879
     3077979.259    13820092.545     3077915.898     13820088.82
     3076250.082    13819791.659
#Sta/Elev= 30
       0   62.66   255.2    62.3  363.28   63.17  425.03   62.12  455.91   62.65
  501.53   61.39  607.19    63.2 1210.97   64.04 1377.01   62.49  1392.1   63.14
 1437.39   61.15 1484.55   60.98 1606.93   63.18 1623.55    62.7 1637.25   54.73
 1637.71   49.75 1642.55   49.71 1647.22   49.72 1647.81   54.83 1661.77   62.86
  2074.9   65.11 2168.41   63.85 2318.68   65.14 2394.87   63.94 2486.29   65.89
 2867.21   65.06 2943.39   63.13 3019.58    65.4 3324.31    65.4 3357.24   66.21
#Mann= 3 , 0 , 0
       0     .15       0 1623.55    .015       0 1661.77     .15       0
#XS Ineff= 2 , 0
       0 1400.73   66.19 1971.93       0   66.23
Permanent Ineff=
       T       T
Bank Sta=1623.55,1661.77
XS Rating Curve= 0
Exp/Cntr=.5,.3

Type RM Length L Ch R = 3 ,10332   ,,,
BEGIN DESCRIPTION:
Leader Bridge
END DESCRIPTION:
Bridge Culvert--1,0,-1,-1, 0
Deck Dist Width WeirC Skew NumUp NumDn MinLoCord MaxHiCord MaxSubmerge Is_Ogee
5,30,2.6,0, 5, 5, , , .95, 0, 0,0,,
 1623.54 1627.34 1642.34 1657.34 1661.86
   62.69   63.13   62.91   63.07   62.83
       0   60.83   60.61   60.77       0
 1600.55 1604.34 1619.34 1634.34 1638.86
   62.66   63.13   62.91   63.07   62.83
       0   60.83   60.61   60.77       0
BR Coef=-1 , 0 , 0 ,, 0 ,,,.8,-1,,0,
WSPro=,,,, 1 ,,,, 0 ,,,, 0 ,,,,-1 ,-1 ,-1 , 0 , 0 , 0 , 0 , 0
BC Design=,, 0 ,, 0 ,,,,,,

Type RM Length L Ch R = 1 ,10314   ,35.89,34.87,33.47
BEGIN DESCRIPTION:
             10338.12
END DESCRIPTION:
XS GIS Cut Line= 5
     3079549.983    13820065.539     3079112.235    13820182.922
     3077988.602    13820056.589      3077925.24    13820052.863
     3076248.722    13819753.193
#Sta/Elev= 30
       0   62.69  230.34   62.27  362.85   63.17  447.76   62.69   493.2    61.4
  583.77   63.23  1036.6   63.15 1383.77   64.21 1398.87   63.65 1413.96   61.37
 1444.15   61.07 1518.18   64.12 1600.55    62.7 1614.25   54.73 1614.71   49.75
 1619.55   49.71 1624.22   49.72 1624.81   54.83 1638.77   62.86 1780.22    61.4
 1838.11    63.3 1975.25   64.56 2373.95   64.46 2493.34   66.03 2569.52   65.17
 2874.28   65.23 2919.99   62.89 2950.47   63.13  3004.8   65.56 3350.49   66.15
#Mann= 3 , 0 , 0
       0     .15       0 1600.55    .015       0 1638.77     .15       0
#XS Ineff= 2 , 0
       0 1389.26          1950.1       0   66.07
Permanent Ineff=
       T       T
Bank Sta=1600.55,1638.77
XS Rating Curve= 0
Exp/Cntr=.5,.3

Type RM Length L Ch R = 1 ,10279   ,830.99,756.08,701.5
BEGIN DESCRIPTION:
             10303.25
END DESCRIPTION:
XS GIS Cut Line= 5
     3079536.031    13820037.647     3079118.485    13820149.979
     3077994.851    13820023.645      3077931.49     13820019.92
     3076247.552    13819720.089
#Sta/Elev= 30
       0   62.68  215.95   61.89  325.09   63.16  508.86   61.19  569.23   63.08
 1354.15   64.17 1405.74   61.23  1474.9   64.13 1520.19   64.61 1550.38   64.49
  1558.8   63.06 1576.55    62.7 1590.25   54.73 1590.71   49.75 1595.55   49.71
 1600.22   49.72 1600.81   54.83 1614.77   62.86 1659.41   63.69 1747.44   61.19
 1838.85   61.18 2052.16   64.48 2372.11   64.17 2463.53   65.45 2676.83   65.64
 2844.42   65.43 2935.84   63.01 2951.07   64.19 3042.49   65.61    3337   65.88
#Mann= 3 , 0 , 0
       0     .15       0 1576.55    .015       0 1614.77     .15       0
#XS Ineff= 2 , 0
       0 1352.26         1993.76       0   66.07
Permanent Ineff=
       T       T
Bank Sta=1576.55,1614.77
XS Rating Curve= 0
Exp/Cntr=.3,.1

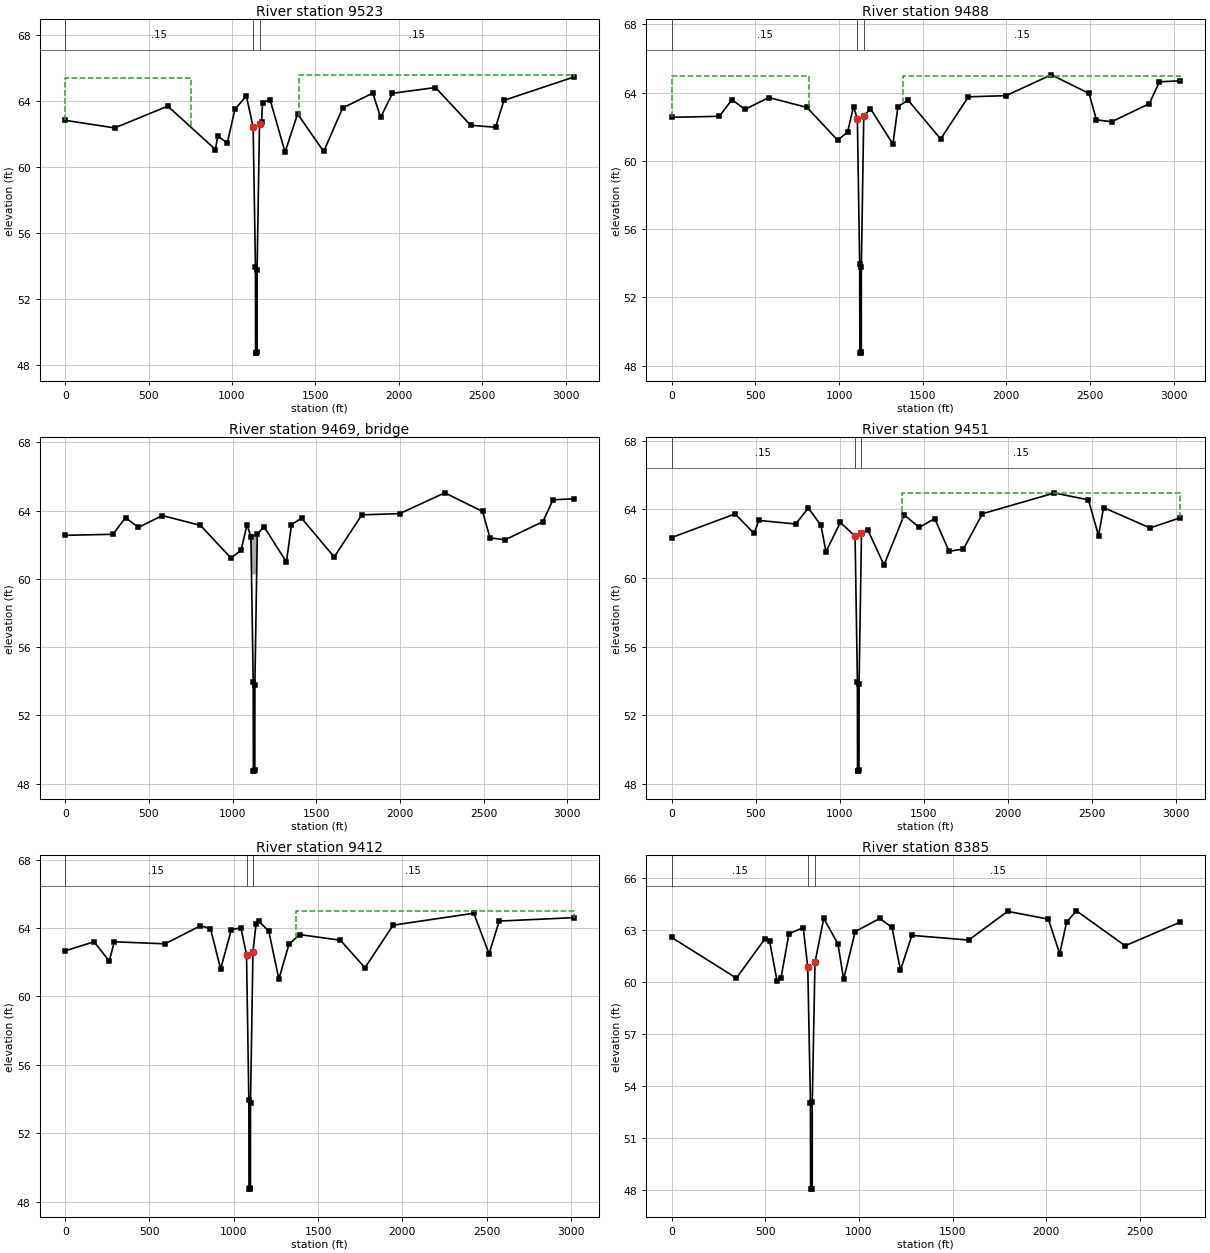
Type RM Length L Ch R = 1 ,9523    ,35.05,35.03,35.33
BEGIN DESCRIPTION:
             9547.179
END DESCRIPTION:
XS GIS Cut Line= 4
     3079278.682    13819232.401     3078173.164     13819290.28
     3078110.798     13819284.82     3076235.932    13819391.398
#Sta/Elev= 30
       0   62.85  296.59   62.39  614.97   63.71  900.44   61.08  914.71   61.89
   971.8   61.48 1017.57   63.52 1085.99   64.33 1126.65   62.45 1140.51   53.94
 1141.43   48.76 1145.35   48.73 1150.09   48.78 1150.42   53.79 1164.84   62.61
 1177.22   62.74 1182.96   63.92 1228.03   64.11 1318.17   60.92 1393.06   63.24
 1549.66   60.96 1663.39    63.6 1844.02    64.5 1890.85   63.03 1961.93   64.49
 2219.63   64.84 2431.06   62.55 2580.21   62.43 2630.08   64.06 3047.53   65.47
#Mann= 3 , 0 , 0
       0     .15       0 1126.65    .015       0 1164.84     .15       0
#XS Ineff= 2 , 0
       0  756.76    65.4 1400.73       0   65.61
Permanent Ineff=
       T       T
Bank Sta=1126.65,1164.84
XS Rating Curve= 0
Exp/Cntr=.5,.3

Type RM Length L Ch R = 1 ,9488    ,39.17,37.47,37.33
BEGIN DESCRIPTION:
             9512.151
END DESCRIPTION:
XS GIS Cut Line= 4
     3079267.455    13819197.943     3078173.768      13819255.2
     3078111.338     13819249.73     3076234.695    13819356.418
#Sta/Elev= 30
       0   62.55  285.35   62.61  360.45   63.59  437.25   63.01  579.98   63.71
  808.36   63.13  991.31   61.21    1051   61.68 1086.61   63.18 1109.65   62.45
 1123.51   53.94 1124.43   48.76 1128.35   48.73 1133.09   48.78 1133.42   53.79
 1147.84   62.61 1187.81   63.06 1321.96   60.98 1352.01   63.17  1412.1   63.56
 1607.42   61.28 1772.68   63.75 1998.12   63.82 2268.48   65.04 2493.85   63.95
 2538.33    62.4 2629.06   62.29 2854.43   63.35 2914.52   64.63 3037.53   64.69
#Mann= 3 , 0 , 0
       0     .15       0 1109.65    .015       0 1147.84     .15       0
#XS Ineff= 2 , 0
       0  818.61   64.97 1382.54       0   64.97
Permanent Ineff=
       T       T
Bank Sta=1109.65,1147.84
XS Rating Curve= 0
Exp/Cntr=.5,.3

Type RM Length L Ch R = 3 ,9469    ,,,
BEGIN DESCRIPTION:
Neff St.
END DESCRIPTION:
Bridge Culvert--1,0,-1,-1, 0
Deck Dist Width WeirC Skew NumUp NumDn MinLoCord MaxHiCord MaxSubmerge Is_Ogee
3.5,30,2.6,0, 5, 5, , , .95, 0, 0,0,,
 1109.65 1113.22 1131.72 1144.22 1147.84
   62.45   62.58   62.54   62.58   62.61
       0   60.28   60.24   60.28       0
 1091.65 1095.22 1113.72 1126.22 1129.84
   62.44   62.58   62.54   62.58   62.61
       0   60.28   60.24   60.28       0
BR Coef=-1 , 0 , 0 ,, 0 ,,,.8,-1,,0,
WSPro=,,,, 1 ,,,, 0 ,,,, 0 ,,,,-1 ,-1 ,-1 , 0 , 0 , 0 , 0 , 0
BC Design=,, 0 ,, 0 ,,,,,,

Type RM Length L Ch R = 1 ,9451    ,37.15,38.42,38.13
BEGIN DESCRIPTION:
             9474.685
END DESCRIPTION:
XS GIS Cut Line= 4
     3079254.554    13819158.346     3078176.584    13819216.556
     3078114.008    13819213.015     3076233.275    13819316.233
#Sta/Elev= 30
       0   62.36   377.6   63.74  490.47    62.6  518.98   63.36  738.13   63.15
  813.24   64.08  888.35   63.08  918.39   61.53 1003.55   63.24 1091.65   62.45
 1105.51   53.94 1106.43   48.76 1110.35   48.73 1115.09   48.78 1115.42   53.79
 1129.84   62.61 1166.89   62.82 1263.91   60.76 1384.09   63.68 1474.22   62.95
 1565.64   63.47 1651.09   61.56 1736.53   61.69 1849.79   63.75 2277.69   64.96
 2480.74   64.56 2540.83   62.47 2570.87   64.11 2847.33   62.92 3025.78   63.51
#Mann= 3 , 0 , 0
       0     .15       0 1091.65    .015       0 1129.84     .15       0
#XS Ineff= 2 , 0
       0  870.38         1371.62       0   64.97
Permanent Ineff=
       T       T
Bank Sta=1091.65,1129.84
XS Rating Curve= 0
Exp/Cntr=.5,.3

Type RM Length L Ch R = 1 ,9412    ,1069.57,1027.17,987.31
BEGIN DESCRIPTION:
             9436.265
END DESCRIPTION:
XS GIS Cut Line= 4
     3079243.395    13819124.097     3078175.071    13819178.081
     3078112.494     13819174.54     3076232.045    13819281.447
#Sta/Elev= 30
       0   62.67  171.11    63.2  261.23   62.07  291.27    63.2  591.65   63.08
  801.92   64.13  861.99   63.97  922.07   61.61   985.8   63.91 1042.22   64.01
 1075.65   62.45 1089.51   53.94 1090.43   48.76 1094.35   48.73 1099.09   48.78
 1099.42   53.79 1113.84   62.61 1132.36   64.26 1147.38   64.41 1207.48   63.83
 1267.58   61.02 1327.67   63.06 1391.05   63.62 1632.72   63.29  1778.4   61.68
 1945.48   64.17 2424.44   64.87 2514.59   62.49 2574.68   64.41 3015.85   64.61
#Mann= 3 , 0 , 0
       0     .15       0 1075.65    .015       0 1113.84     .15       0
#XS Ineff= 2 , 0
       0  845.38         1371.62       0   65.01
Permanent Ineff=
       T       T
Bank Sta=1075.65,1113.84
XS Rating Curve= 0
Exp/Cntr=.3,.1

Type RM Length L Ch R = 1 ,8385    ,34.97,35.08,35.14
BEGIN DESCRIPTION:
             8409.098
END DESCRIPTION:
XS GIS Cut Line= 4
     3078879.914    13818008.487      3078178.02    13818148.389
     3078113.815     13818155.52     3076202.815    13818454.604
#Sta/Elev= 30
       0   62.58  345.55   60.23  498.58   62.51  522.49    62.4  562.35   60.09
  583.67   60.23  626.12   62.79  702.63   63.15  726.79   60.85  741.09   53.03
  741.81   48.03  750.66   48.05  750.83   53.05  765.35   61.14     812   63.68
  887.91   62.21  918.28   60.16   980.1   62.92 1111.38   63.68 1176.38   63.16
 1221.93   60.69 1282.66    62.7 1586.31   62.43 1794.04   64.09 2011.42   63.64
 2072.15   61.64 2109.11   63.47 2161.62   64.12 2421.35    62.1 2714.56   63.46
#Mann= 3 , 0 , 0
       0     .15       0  726.79    .015       0  765.35     .15       0
#XS Ineff= 2 , 0
       0  507.93          995.93       0
Permanent Ineff=
       T       T
Bank Sta=726.79,765.35
XS Rating Curve= 0
Exp/Cntr=.5,.3

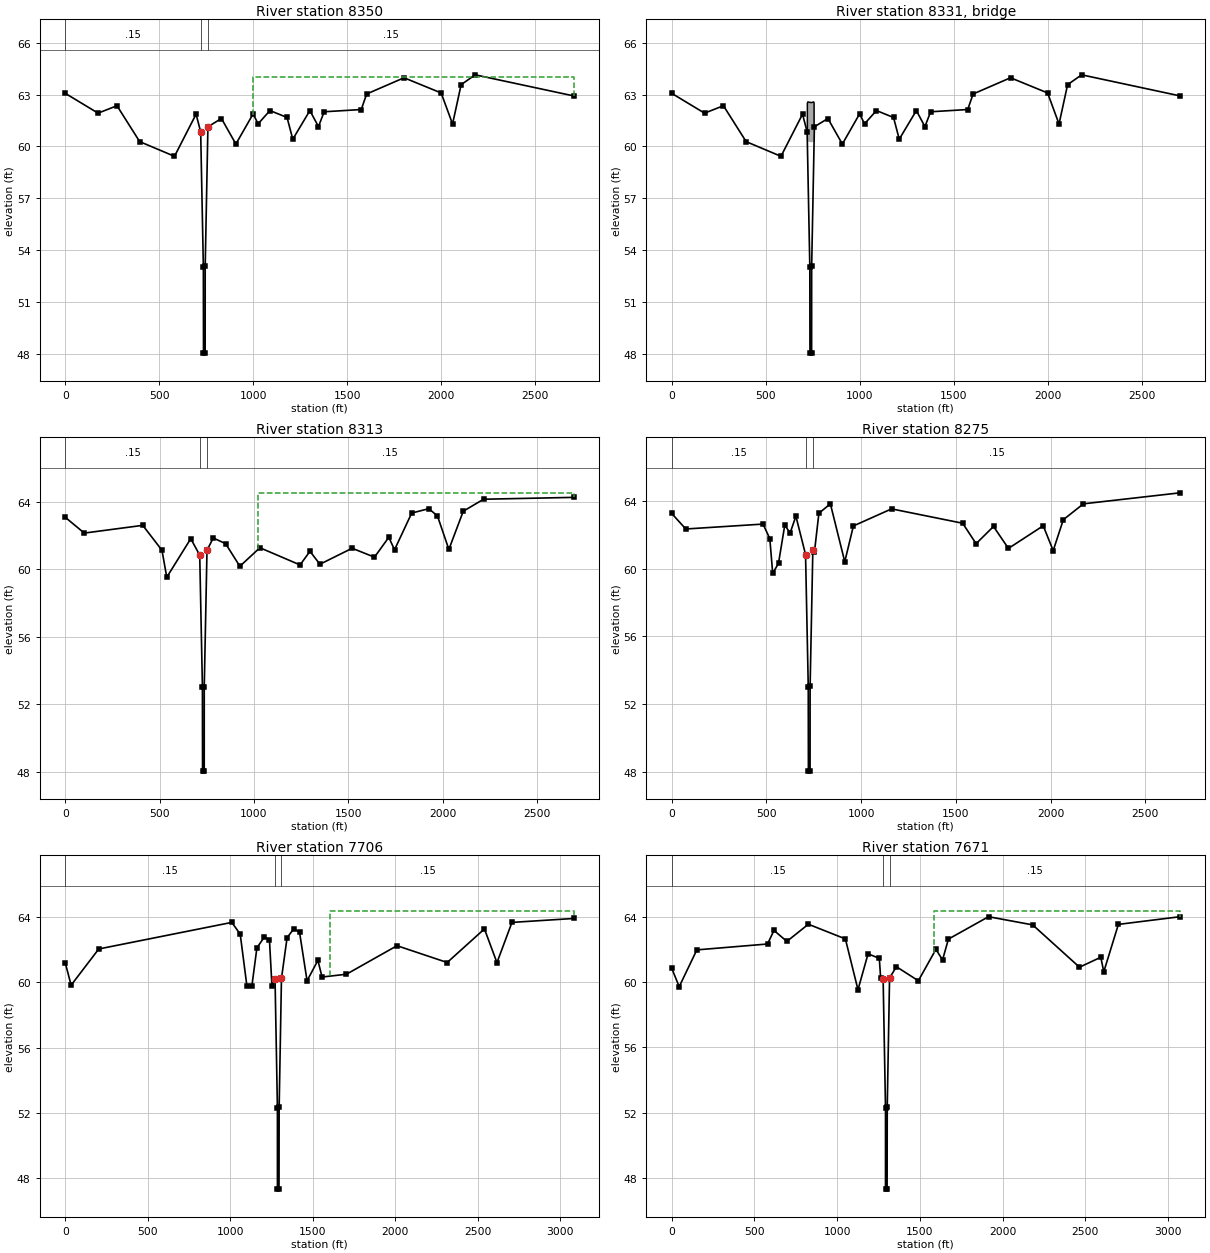
Type RM Length L Ch R = 1 ,8350    ,38.01,37.11,37.77
BEGIN DESCRIPTION:
             8374.017
END DESCRIPTION:
XS GIS Cut Line= 4
     3078868.999    13817974.985     3078173.792    13818113.629
     3078109.587     13818120.76     3076201.569     13818419.37
#Sta/Elev= 30
       0   63.08  174.88   61.93  275.46   62.36  396.34   60.28  581.51   59.43
  696.28   61.87  720.79   60.85  735.09   53.03  735.81   48.03  744.66   48.05
  744.83   53.05  759.35   61.14  831.28   61.62  908.13   60.14 1000.02   61.89
 1026.28   61.31 1089.38   62.08 1180.48   61.68 1210.84   60.42 1301.94   62.08
 1347.49   61.15 1377.85   62.01 1575.23   62.14 1603.91   63.04 1802.96   63.98
 2000.34    63.1 2061.07    61.3 2106.62   63.58 2181.54   64.15 2704.74   62.93
#Mann= 3 , 0 , 0
       0     .15       0  720.79    .015       0  759.35     .15       0
#XS Ineff= 2 , 0
       0  497.93          997.92       0   64.05
Permanent Ineff=
       T       T
Bank Sta=720.79,759.35
XS Rating Curve= 0
Exp/Cntr=.5,.3

Type RM Length L Ch R = 3 ,8331    ,,,
BEGIN DESCRIPTION:
Sharpview Bridge
END DESCRIPTION:
Bridge Culvert--1,0,-1,-1, 0
Deck Dist Width WeirC Skew NumUp NumDn MinLoCord MaxHiCord MaxSubmerge Is_Ogee
5,30,2.6,0, 9, 9, , , .95, 0, 0,0,,
     720  721.95  721.95  724.42  742.92  755.42  757.81  757.81  759.36
    60.8    60.8   62.49   62.58   62.54   62.58   62.52   61.14   61.14
                       0   60.28   60.24   60.28       0
  712.79  713.95  713.95  716.42  734.92  747.42  749.81  749.81  751.36
    60.8    60.8   62.49   62.58   62.54   62.58   62.52   61.14   61.14
                       0   60.28   60.24   60.28       0
BR Coef=-1 , 0 , 0 ,, 0 ,,,.8,-1,,0,
WSPro=,,,, 1 ,,,, 0 ,,,, 0 ,,,,-1 ,-1 ,-1 , 0 , 0 , 0 , 0 , 0
BC Design=,, 0 ,, 0 ,,,,,,

Type RM Length L Ch R = 1 ,8313    ,36.93,38.08,37.53
BEGIN DESCRIPTION:
             8336.906
END DESCRIPTION:
XS GIS Cut Line= 4
     3078856.523    13817936.693     3078168.417    13818076.957
     3078104.212    13818084.088     3076200.146    13818379.118
#Sta/Elev= 30
       0    63.1  101.06   62.16  411.02   62.62  512.75   61.14  538.18   59.54
  665.34   61.83  712.79   60.85  727.09   53.03  727.81   48.03  736.66   48.05
  736.83   53.05  751.35   61.14  784.49   61.87   850.2   61.53  925.44   60.19
 1031.69   61.29 1244.48   60.27 1297.05   61.08 1349.62   60.31 1520.47   61.26
 1638.76   60.73 1714.75   61.91  1745.1   61.17 1836.18   63.35 1927.25   63.61
 1972.79   63.17 2033.03   61.19  2109.4   63.46 2217.03   64.17 2693.64   64.28
#Mann= 3 , 0 , 0
       0     .15       0  712.79    .015       0  751.35     .15       0
#XS Ineff= 2 , 0
       0  486.93         1022.87       0   64.55
Permanent Ineff=
       T       T
Bank Sta=712.79,751.35
XS Rating Curve= 0
Exp/Cntr=.5,.3

Type RM Length L Ch R = 1 ,8275    ,568.09,568.8,572.22
BEGIN DESCRIPTION:
             8298.831
END DESCRIPTION:
XS GIS Cut Line= 4
     3078845.608    13817903.191     3078164.731    13818039.129
     3078100.526     13818046.26     3076198.901    13818343.888
#Sta/Elev= 30
       0   63.28   74.55   62.36  482.32   62.65  518.14   61.79  533.43   59.73
  564.02   60.33  597.07   62.59  625.21   62.12   655.8   63.12  706.79   60.85
  721.09   53.03  721.81   48.03  730.66   48.05  730.83   53.05  745.35   61.14
  753.72   60.99  777.16   63.29  837.89   63.85   913.8   60.42  959.35   62.54
 1160.86   63.55 1536.29    62.7 1607.21   61.49 1699.11   62.51 1777.87   61.21
 1961.66   62.55 2014.18   61.08 2067.68   62.91 2173.96   63.85 2683.69    64.5
#Mann= 3 , 0 , 0
       0     .15       0  706.79    .015       0  745.35     .15       0
#XS Ineff= 2 , 0
       0  477.93          968.93       0
Permanent Ineff=
       T       T
Bank Sta=706.79,745.35
XS Rating Curve= 0
Exp/Cntr=.3,.1

Type RM Length L Ch R = 1 ,7706    ,35.26,35.16,35.11
BEGIN DESCRIPTION:
              7730.03
END DESCRIPTION:
XS GIS Cut Line= 4
     3079287.908    13817268.163     3078033.569    13817482.957
     3077971.206     13817495.18     3076242.815    13817737.774
#Sta/Elev= 30
       0   61.21   35.92   59.83  203.33   62.05  1009.9   63.68  1060.9   62.96
 1101.21    59.8 1131.64   59.78 1162.08   62.12 1207.74   62.79 1238.17    62.6
 1253.39   59.77 1272.05   60.19 1286.41    52.3 1286.45   47.35 1296.07   47.32
  1296.9   52.34 1310.92   60.24 1344.94   62.74 1385.76   63.29 1420.67   63.07
 1466.11    60.1 1531.87   61.35    1557   60.33 1704.54    60.5 2011.41   62.25
 2315.55   61.22 2541.35   63.28 2617.29   61.21 2708.17   63.68 3081.48   63.92
#Mann= 3 , 0 , 0
       0     .15       0 1272.05    .015       0 1310.92     .15       0
#XS Ineff= 2 , 0
       0  1047.4         1604.47       0   64.39
Permanent Ineff=
       T       T
Bank Sta=1272.05,1310.92
XS Rating Curve= 0
Exp/Cntr=.5,.3

Type RM Length L Ch R = 1 ,7671    ,38.8,38.69,38.96
BEGIN DESCRIPTION:
             7694.873
END DESCRIPTION:
XS GIS Cut Line= 4
     3079282.435    13817233.593     3078028.096    13817448.387
     3077965.733     13817460.61     3076246.354    13817701.933
#Sta/Elev= 30
       0   60.84   45.59   59.71  152.12   61.96  579.37   62.32  618.35   63.15
  696.31   62.48  826.24   63.53    1050   62.63 1126.09   59.52 1186.96   61.72
 1255.02   61.44 1263.06   60.23 1278.05   60.19 1292.41    52.3 1292.45   47.35
 1302.07   47.32  1302.9   52.34 1316.92   60.24 1358.39   60.93 1490.88   60.07
 1596.91   61.99 1637.33   61.35 1672.65   62.62    1915   63.99 2181.92   63.49
 2464.91    60.9 2593.69   61.51 2611.76   60.62 2699.95   63.52 3072.38   63.99
#Mann= 3 , 0 , 0
       0     .15       0 1278.05    .015       0 1316.92     .15       0
#XS Ineff= 2 , 0
       0  1058.4         1586.28       0   64.35
Permanent Ineff=
       T       T
Bank Sta=1278.05,1316.92
XS Rating Curve= 0
Exp/Cntr=.5,.3

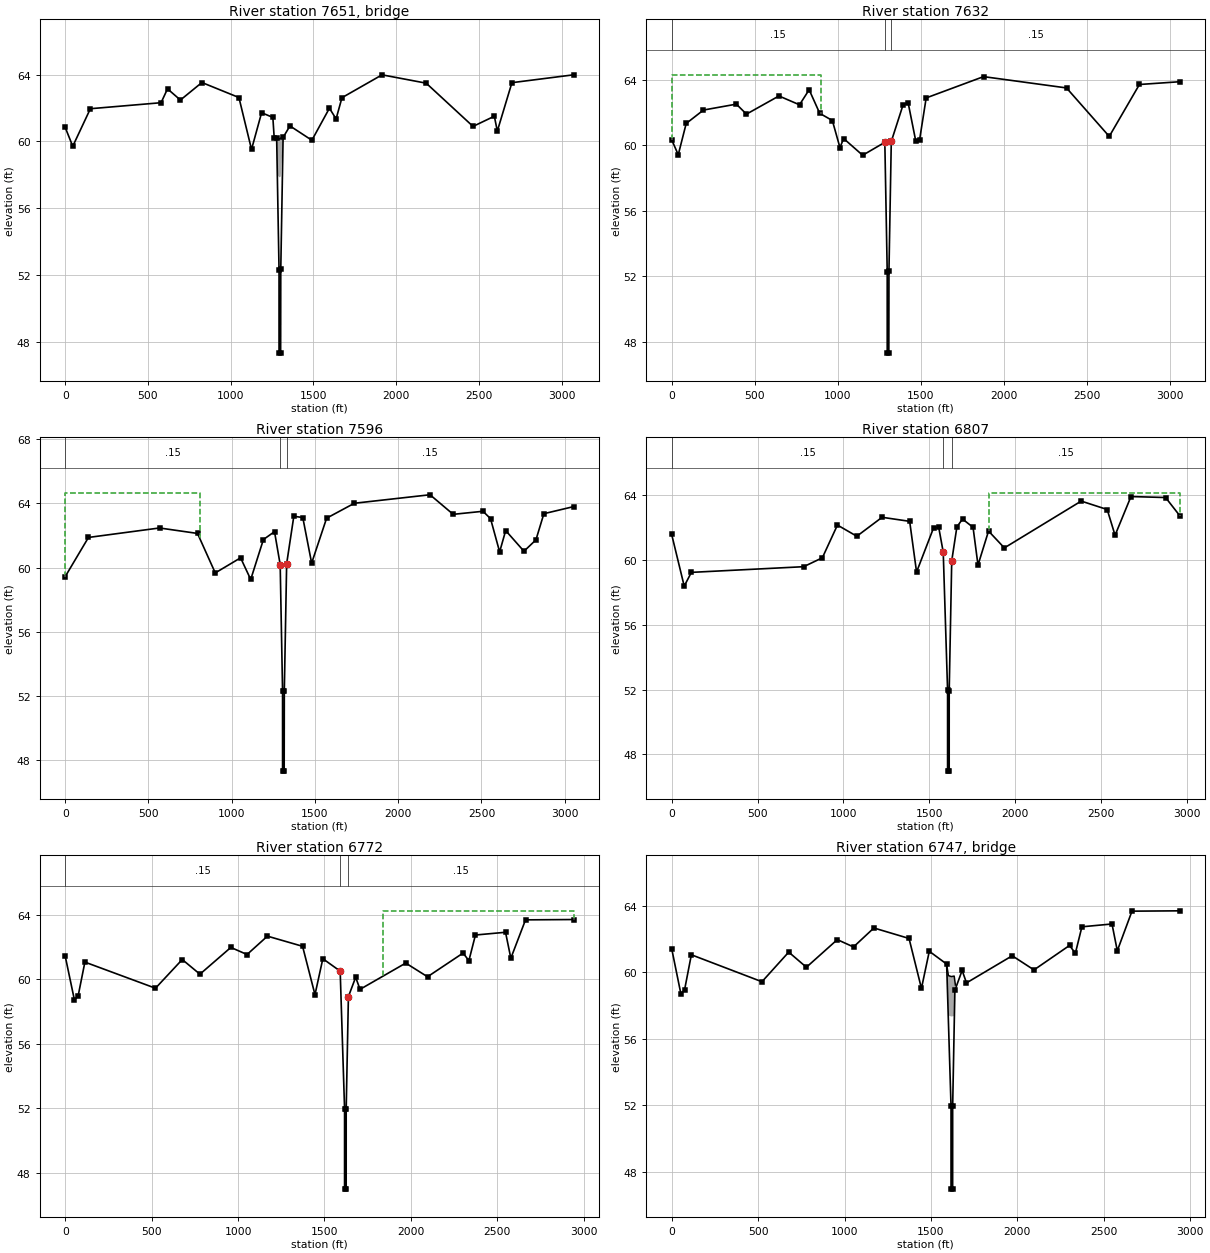
Type RM Length L Ch R = 3 ,7651    ,,,
BEGIN DESCRIPTION:
Carvel Bridge
END DESCRIPTION:
Bridge Culvert--1,0,-1,-1, 0
Deck Dist Width WeirC Skew NumUp NumDn MinLoCord MaxHiCord MaxSubmerge Is_Ogee
5,30,2.6,0, 5, 5, , , .95, 0, 0,0,,
 1277.16    1282 1294.82 1316.82    1317
   60.17   60.24   60.15   60.28   60.23
       0   57.94   57.85   57.98       0
 1282.16 1287.82 1299.82 1321.82    1323
   60.17   60.24   60.15   60.28   60.23
       0   57.94   57.85   57.98       0
BR Coef=-1 , 0 , 0 ,, 0 ,,,.8,-1,,0,
WSPro=,,,, 1 ,,,, 0 ,,,, 0 ,,,,-1 ,-1 ,-1 , 0 , 0 , 0 , 0 , 0
BC Design=,, 0 ,, 0 ,,,,,,

Type RM Length L Ch R = 1 ,7632    ,36.77,36.66,36.28
BEGIN DESCRIPTION:
             7656.189
END DESCRIPTION:
XS GIS Cut Line= 4
      3079276.54     13817195.53     3078022.201    13817410.325
     3077959.838    13817422.547     3076250.397    13817660.978
#Sta/Elev= 30
       0   60.35   39.61   59.43    87.5   61.34  191.44   62.16  389.63   62.52
   450.5   61.91  646.21   63.02  770.09   62.48  828.12    63.4  891.84   61.96
  967.93   61.52 1013.58   59.87 1036.01   60.42 1150.55    59.4 1284.05   60.19
 1298.41    52.3 1298.45   47.35 1308.07   47.32  1308.9   52.34 1322.92   60.24
 1394.04   62.48 1424.33   62.61 1469.77    60.3 1493.24   60.33 1533.12    62.9
 1878.69    64.2 2378.48   63.51 2635.95   60.55 2817.69   63.72 3062.14   63.89
#Mann= 3 , 0 , 0
       0     .15       0 1284.05    .015       0 1322.92     .15       0
#XS Ineff= 2 , 0
       0  902.29   64.31  1559.4       0
Permanent Ineff=
       T       T
Bank Sta=1284.05,1322.92
XS Rating Curve= 0
Exp/Cntr=.5,.3

Type RM Length L Ch R = 1 ,7596    ,763.34,788.28,762.49
BEGIN DESCRIPTION:
             7619.525
END DESCRIPTION:
XS GIS Cut Line= 4
     3079270.708    13817159.503     3078016.369    13817374.297
     3077954.006     13817386.52     3076253.937    13817625.123
#Sta/Elev= 30
       0   59.44  139.64   61.88  566.33   62.47  794.61   62.13  901.14   59.67
 1053.32   60.61 1114.14   59.26 1190.29   61.75 1257.07   62.24 1291.05   60.19
 1305.41    52.3 1305.45   47.35 1315.07   47.32  1315.9   52.34 1329.92   60.24
 1373.01    63.2  1426.9   63.12 1480.03   60.28 1569.92   63.08 1736.54   64.01
 2190.95   64.54 2330.13   63.32 2509.04   63.51 2554.48   63.05 2609.07   60.98
 2645.36   62.31 2755.18   61.02 2827.12   61.73 2874.72   63.36 3052.88    63.8
#Mann= 3 , 0 , 0
       0     .15       0 1291.05    .015       0 1329.92     .15       0
#XS Ineff= 2 , 0
       0  807.69   64.66  1567.4       0
Permanent Ineff=
       T       T
Bank Sta=1291.05,1329.92
XS Rating Curve= 0
Exp/Cntr=.3,.1

Type RM Length L Ch R = 1 ,6807    ,35.33,35.85,35.46
BEGIN DESCRIPTION:
             6831.243
END DESCRIPTION:
XS GIS Cut Line= 4
      3079339.92     13816421.31      3077763.62    13816626.536
     3077707.108      13816632.3     3076423.039    13816913.099
#Sta/Elev= 30
       0   61.58   73.03   58.39  114.76   59.24  768.85   59.59  877.65   60.14
   965.5   62.16 1078.41   61.47 1225.63   62.64 1386.24   62.39 1426.39   59.26
 1525.18   61.98 1555.44   62.02 1581.72   60.49 1607.08   51.95 1607.12   46.97
  1616.4      47  1616.5   51.94 1631.22   59.95 1661.36   62.05 1694.16   62.53
 1755.44   62.02  1784.2   59.69 1845.62   61.79 1937.74   60.75  2385.4   63.64
 2536.73   63.12 2582.63   61.53 2675.19   63.92 2876.77   63.86 2960.82   62.72
#Mann= 3 , 0 , 0
       0     .15       0 1581.72    .015       0 1631.22     .15       0
#XS Ineff= 2 , 0
       0 1364.64         1846.15       0   64.15
Permanent Ineff=
       T       T
Bank Sta=1581.72,1631.22
XS Rating Curve= 0
Exp/Cntr=.5,.3

Type RM Length L Ch R = 1 ,6772    ,50.47,55.66,51.9
BEGIN DESCRIPTION:
             6795.388
END DESCRIPTION:
XS GIS Cut Line= 4
      3079335.39     13816386.61     3077755.888    13816592.066
     3077699.376     13816597.83       3076438.2    13816873.952
#Sta/Elev= 30
       0   61.42   53.34    58.7   74.76   58.95  113.84   61.05  522.25   59.43
   677.1   61.21   779.4    60.3  958.19   61.96 1051.89   61.52 1169.78   62.66
 1373.13   62.03 1444.96   59.03 1490.34   61.26 1590.72   60.49 1616.08   51.95
 1616.12   46.97  1625.4      47  1625.5   51.94 1638.32   58.91 1680.31   60.11
  1705.5   59.36 1970.04   60.99 2096.01   60.14 2301.58   61.61 2335.36   61.14
 2373.15   62.73 2547.26    62.9 2577.97   61.29 2662.89   63.67 2940.66   63.69
#Mann= 3 , 0 , 0
       0     .15       0 1590.72    .015       0 1638.32     .15       0
#XS Ineff= 2 , 0
       0 1379.93         1839.92       0   64.23
Permanent Ineff=
       T       T
Bank Sta=1590.72,1638.32
XS Rating Curve= 0
Exp/Cntr=.5,.3

Type RM Length L Ch R = 3 ,6747    ,,,
BEGIN DESCRIPTION:
Langdon Bridge
END DESCRIPTION:
Bridge Culvert--1,0,-1,-1, 0
Deck Dist Width WeirC Skew NumUp NumDn MinLoCord MaxHiCord MaxSubmerge Is_Ogee
5,30,2.6,0, 5, 5, , , .95, 0, 0,0,,
 1590.72 1600.77 1617.77 1634.27 1641.45
   60.48    59.8   59.74   59.77   59.23
       0    57.4   57.34   57.37       0
 1595.72 1606.27 1623.27 1639.77 1645.23
   60.54    59.8   59.74   59.77   59.93
       0    57.4   57.34   57.37       0
BR Coef=-1 , 0 , 0 ,, 0 ,,,.8,-1,,0,
WSPro=,,,, 1 ,,,, 0 ,,,, 0 ,,,,-1 ,-1 ,-1 , 0 , 0 , 0 , 0 , 0
BC Design=,, 0 ,, 0 ,,,,,,