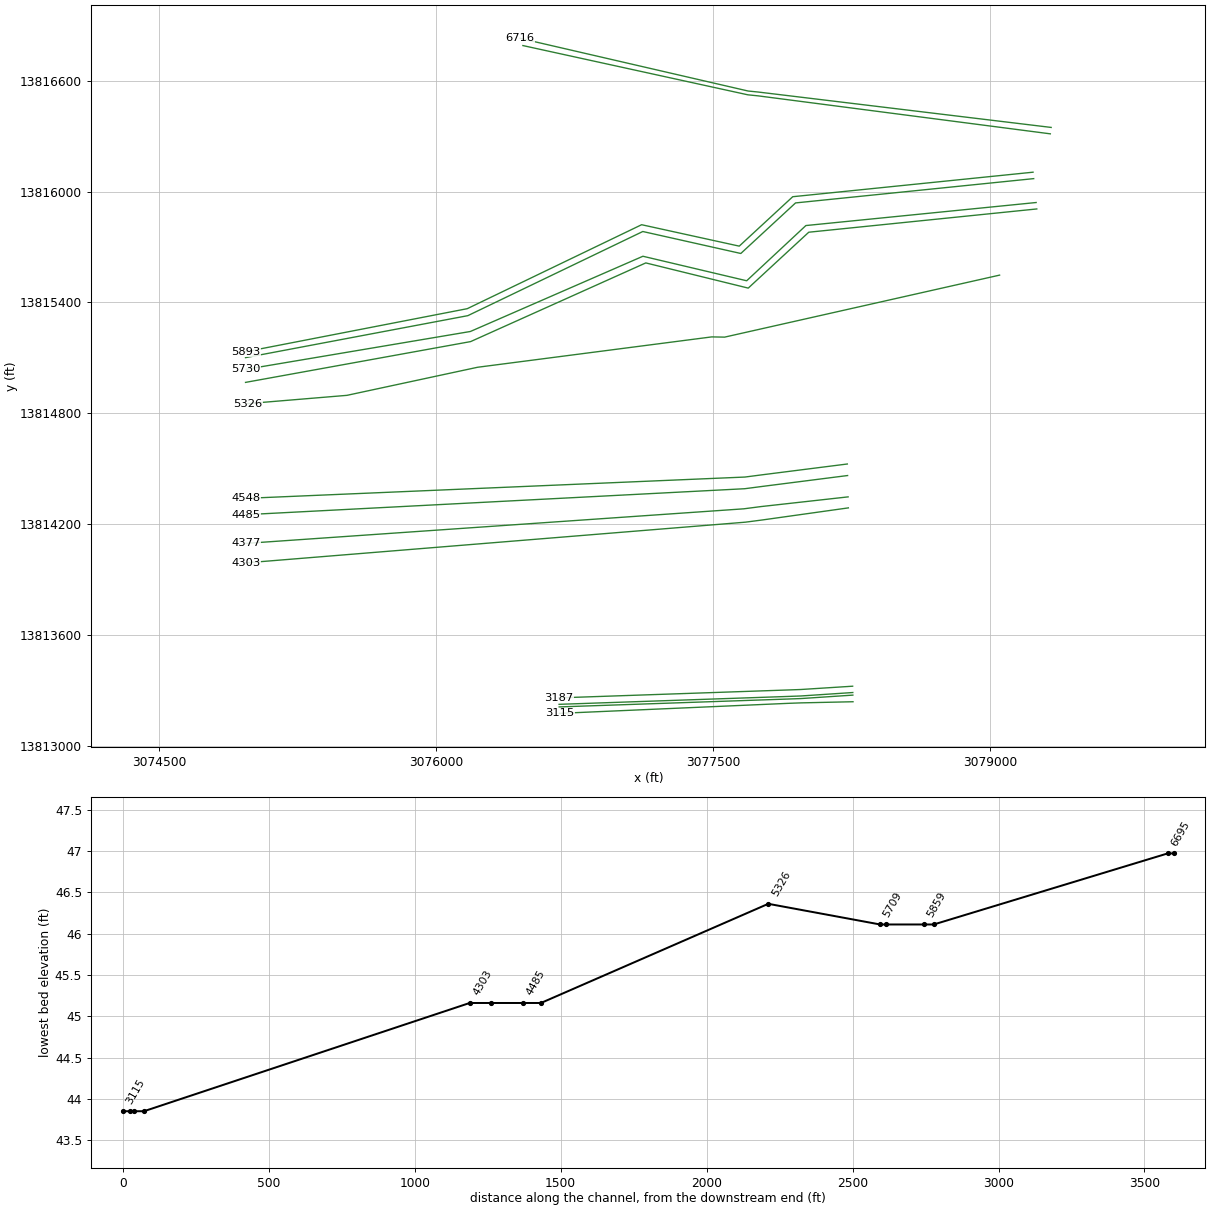
HEC-RAS study D133-00-00.prj: D133-00-00

--- D133-00-00.g01 (geometry) --- (continued)

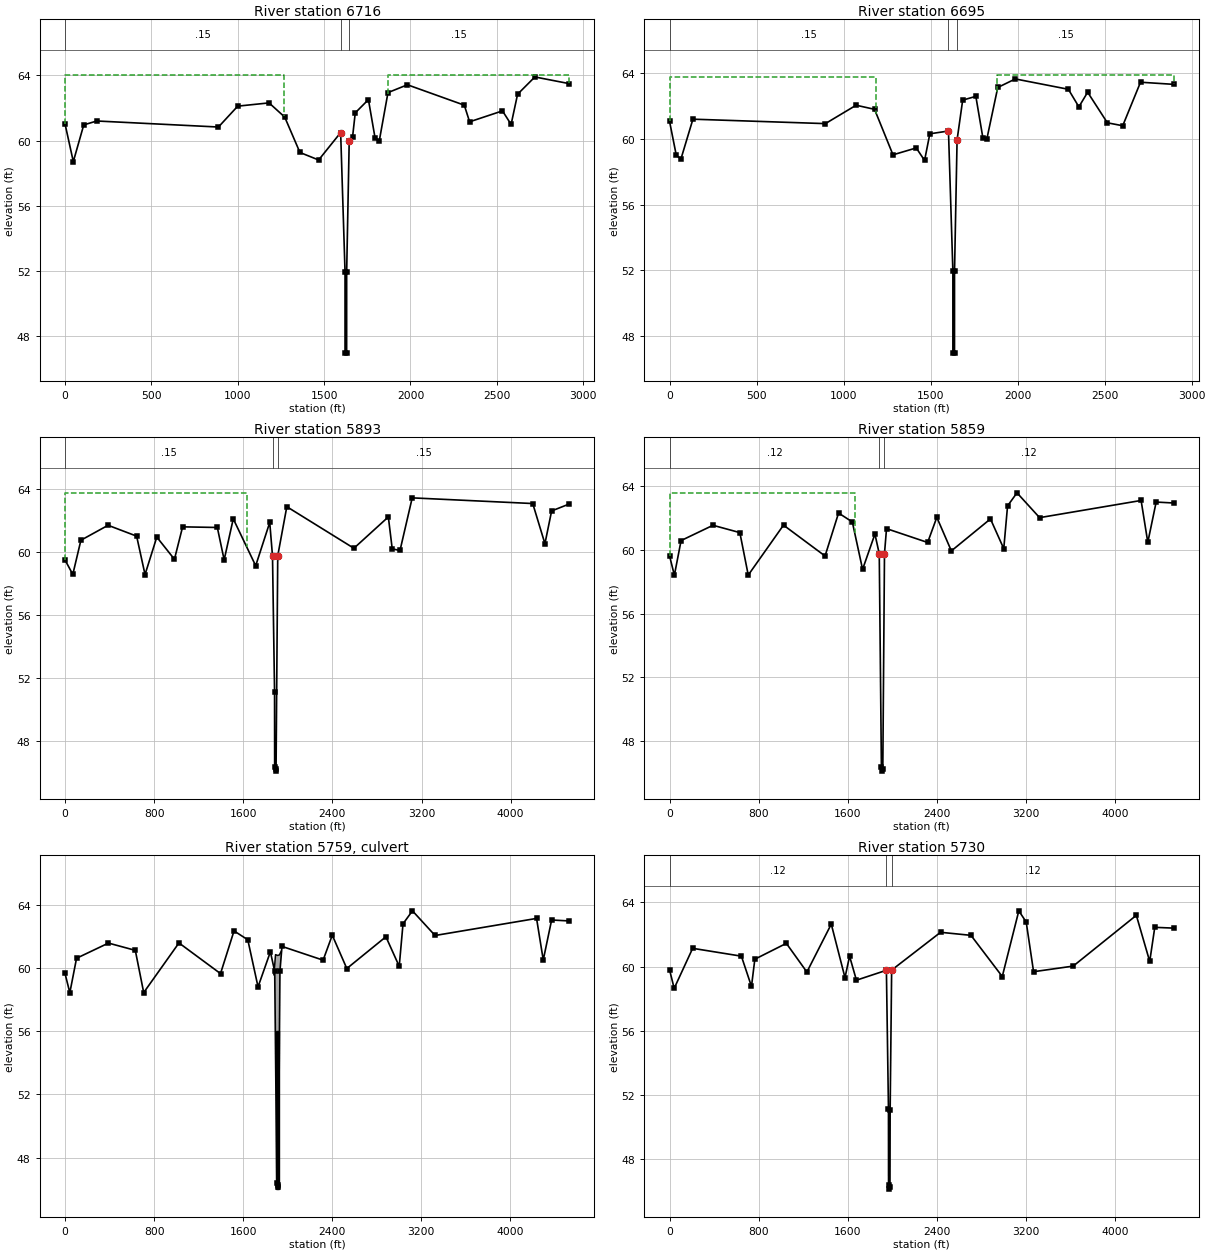
Type RM Length L Ch R = 1 ,6716    ,25.08,21.08,23.53
BEGIN DESCRIPTION:
             6739.727
END DESCRIPTION:
XS GIS Cut Line= 4
      3079330.22     13816346.94     3077746.015    13816538.337
     3077689.503    13816544.101      3076455.53    13816829.202
#Sta/Elev= 30
       0   61.03   48.07   58.71   108.5   60.96  184.05    61.2  888.16   60.83
  999.94   62.11 1181.25   62.31  1271.9   61.44 1359.98   59.27 1468.32   58.81
 1595.72   60.49 1621.08   51.95 1621.12   46.97  1630.4      47  1630.5   51.94
 1645.22   59.95 1664.85   60.24 1680.24    61.7 1756.47   62.51  1794.6   60.18
  1818.8   59.95 1869.63   62.94 1982.18   63.42 2311.45   62.17 2342.24   61.15
 2532.44   61.82 2582.46   60.99 2619.98   62.84 2720.03    63.9 2919.01   63.49
#Mann= 3 , 0 , 0
       0     .15       0 1595.72    .015       0 1645.22     .15       0
#XS Ineff= 2 , 0
       0 1266.11   64.03 1867.98       0   63.99
Permanent Ineff=
       T       T
Bank Sta=1595.72,1645.22
XS Rating Curve= 0
Exp/Cntr=.5,.3

Type RM Length L Ch R = 1 ,6695    ,468.97,801.66,803.92
BEGIN DESCRIPTION:
             6718.653
END DESCRIPTION:
XS GIS Cut Line= 4
      3079325.68     13816312.24     3077744.622    13816517.756
      3077688.11     13816523.52     3076470.691    13816790.055
#Sta/Elev= 30
       0   61.08   38.77   59.01   65.54   58.79   134.3   61.21  895.48   60.94
 1072.12   62.06 1178.01   61.81 1283.89   59.04 1417.54   59.46 1465.41    58.7
 1495.66   60.32 1602.72   60.49 1628.08   51.95 1628.12   46.97  1637.4      47
  1637.5   51.94 1652.22   59.95 1684.41   62.37    1760    62.6 1800.22   60.09
 1822.98   59.99 1885.97   63.14 1986.75   63.66 2291.59   63.03 2352.07   61.96
 2402.46   62.85 2515.83   60.99 2604.02   60.81 2706.19   63.46 2897.42   63.33
#Mann= 3 , 0 , 0
       0     .15       0 1602.72    .015       0 1652.22     .15       0
#XS Ineff= 2 , 0
       0 1188.15   63.79 1880.46       0   63.91
Permanent Ineff=
       T       T
Bank Sta=1602.72,1652.22
XS Rating Curve= 0
Exp/Cntr=.3,.1

Type RM Length L Ch R = 1 ,5893    ,35.49,34.6,35.33
BEGIN DESCRIPTION:
             5916.989
END DESCRIPTION:
XS GIS Cut Line= 6
       3079232.1     13816104.65     3077931.421     13815971.93
     3077641.785      13815704.4     3077113.324    13815820.337
     3076169.361    13815365.818     3074969.429    13815132.727
#Sta/Elev= 30
       0   59.52   69.96    58.6  142.67   60.77   386.6   61.72  642.92   61.03
  718.31   58.59  823.86   60.97  982.23   59.56 1055.54   61.62 1367.22   61.58
 1428.48   59.52 1510.16   62.13 1711.48   59.15 1837.61    61.9 1862.42   59.77
 1880.88   51.13 1881.74   46.39 1889.54   46.11 1894.37   46.27 1909.43   59.78
  1990.9    62.9 2592.96   60.26 2902.11   62.25 2937.02   60.22 3006.85   60.12
 3116.34   63.46  4198.2    63.1 4307.55   60.55 4367.61   62.63 4525.82   63.07
#Mann= 3 , 0 , 0
       0     .15       0 1862.42    .015       0 1909.43     .15       0
#XS Ineff= 2 , 0
       0 1632.02   63.78 1987.23       0
Permanent Ineff=
       T       T
Bank Sta=1862.42,1909.43
XS Rating Curve= 0
Exp/Cntr=.5,.3

Type RM Length L Ch R = 1 ,5859    ,129.56,128.64,129.18
BEGIN DESCRIPTION:
             5882.385
END DESCRIPTION:
XS GIS Cut Line= 6
      3079235.65     13816069.83     3077946.591     13815938.29
     3077650.321     13815664.63     3077119.749     13815783.56
      3076172.79    13815328.105     3074969.429    13815100.833
#Sta/Elev= 30
       0   59.64   43.37   58.42  103.69    60.6  390.17   61.56  631.41    61.1
   706.8   58.43 1023.44   61.57 1396.61   59.63 1517.99   62.33 1641.65   61.77
 1733.72   58.79 1844.57   61.01 1883.42   59.77 1902.74   46.39 1910.54   46.11
 1915.37   46.27 1930.43   59.78 1948.73   61.35 2318.12   60.48 2400.39   62.06
 2531.03   59.95 2882.17   61.96 3001.67   60.09 3035.81   62.78 3120.47    63.6
 3323.57   62.04 4235.19   63.12 4295.27   60.49 4370.38   63.02 4528.69   62.96
#Mann= 3 , 0 , 0
       0     .12       0 1883.42    .015       0 1930.43     .12       0
#XS Ineff= 2 , 0
       0  1663.2   63.57 2018.23       0
Permanent Ineff=
       T       T
Bank Sta=1883.42,1930.43
XS Rating Curve= 0
Exp/Cntr=.5,.3

Type RM Length L Ch R = 2 ,5759    ,,,
BEGIN DESCRIPTION:
Beechnut Culvert
END DESCRIPTION:
Bridge Culvert--1,0,-1,-1, 0
Deck Dist Width WeirC Skew NumUp NumDn MinLoCord MaxHiCord MaxSubmerge Is_Ogee
5,120,2.6,0, 5, 5, , , .95, 0, 0,0,,
 1875.87 1890.92 1908.42 1925.42 1941.38
   59.56   60.83   60.78   60.81   61.04
       0       0       0       0       0
 1945.38 1952.92 1970.42 1987.42 1992.46
   59.73   60.83   60.78   60.81   59.78
       0       0       0       0       0
BR Coef=-1 , 0 , 0 ,, 0 ,,,.8,-1,,0,
WSPro=,,,, 1 ,,,, 0 ,,,, 0 ,,,,-1 ,-1 ,-1 , 0 , 0 , 0 , 0 , 0
Culvert=2,10,10,120,.013,.5,1,8,1,46,1897.42,46,1959.42,Culvert #1  , 0 ,5
Culvert Bottom n=.013
Culvert=2,10,10,120,.013,.5,1,8,1,46,1908.42,46,1970.42,Culvert #2  , 0 ,5
Culvert Bottom n=.013
Culvert=2,10,10,120,.013,.5,1,8,1,46,1919.42,46,1981.42,Culvert #3  , 0 ,5
Culvert Bottom n=.013
BC Design=,, 0 ,, 0 ,,,,,,

Type RM Length L Ch R = 1 ,5730    ,37.75,20.43,33.23
BEGIN DESCRIPTION:
              5753.74
END DESCRIPTION:
XS GIS Cut Line= 6
      3079248.85      13815940.5     3078002.555    13815815.823
     3077682.025     13815516.95     3077120.434    13815649.643
     3076186.503    13815242.396     3074972.324    13815037.794
#Sta/Elev= 30
       0    59.8   41.56   58.64  207.38   61.14  644.55   60.65     735   58.76
  765.15   60.46 1047.86   61.45 1232.12   59.66 1450.85   62.65  1573.9   59.31
 1614.92   60.65 1676.45   59.15 1945.42   59.77 1963.88   51.13 1964.74   46.39
 1972.54   46.11 1977.37   46.27 1978.97   51.03 1992.43   59.78 2431.43   62.14
 2704.12   61.95 2984.92   59.38 3133.35   63.48 3199.65   62.78 3265.72   59.68
 3621.09   60.03 4187.56    63.2 4307.66   60.32 4352.96   62.45 4523.54    62.4
#Mann= 3 , 0 , 0
       0     .12       0 1945.42    .015       0 1992.43     .12       0
#XS Ineff= 2 , 0
       0 1875.23         2115.23       0
Permanent Ineff=
       T       T
Bank Sta=1945.42,1992.43
XS Rating Curve= 0
Exp/Cntr=.5,.3

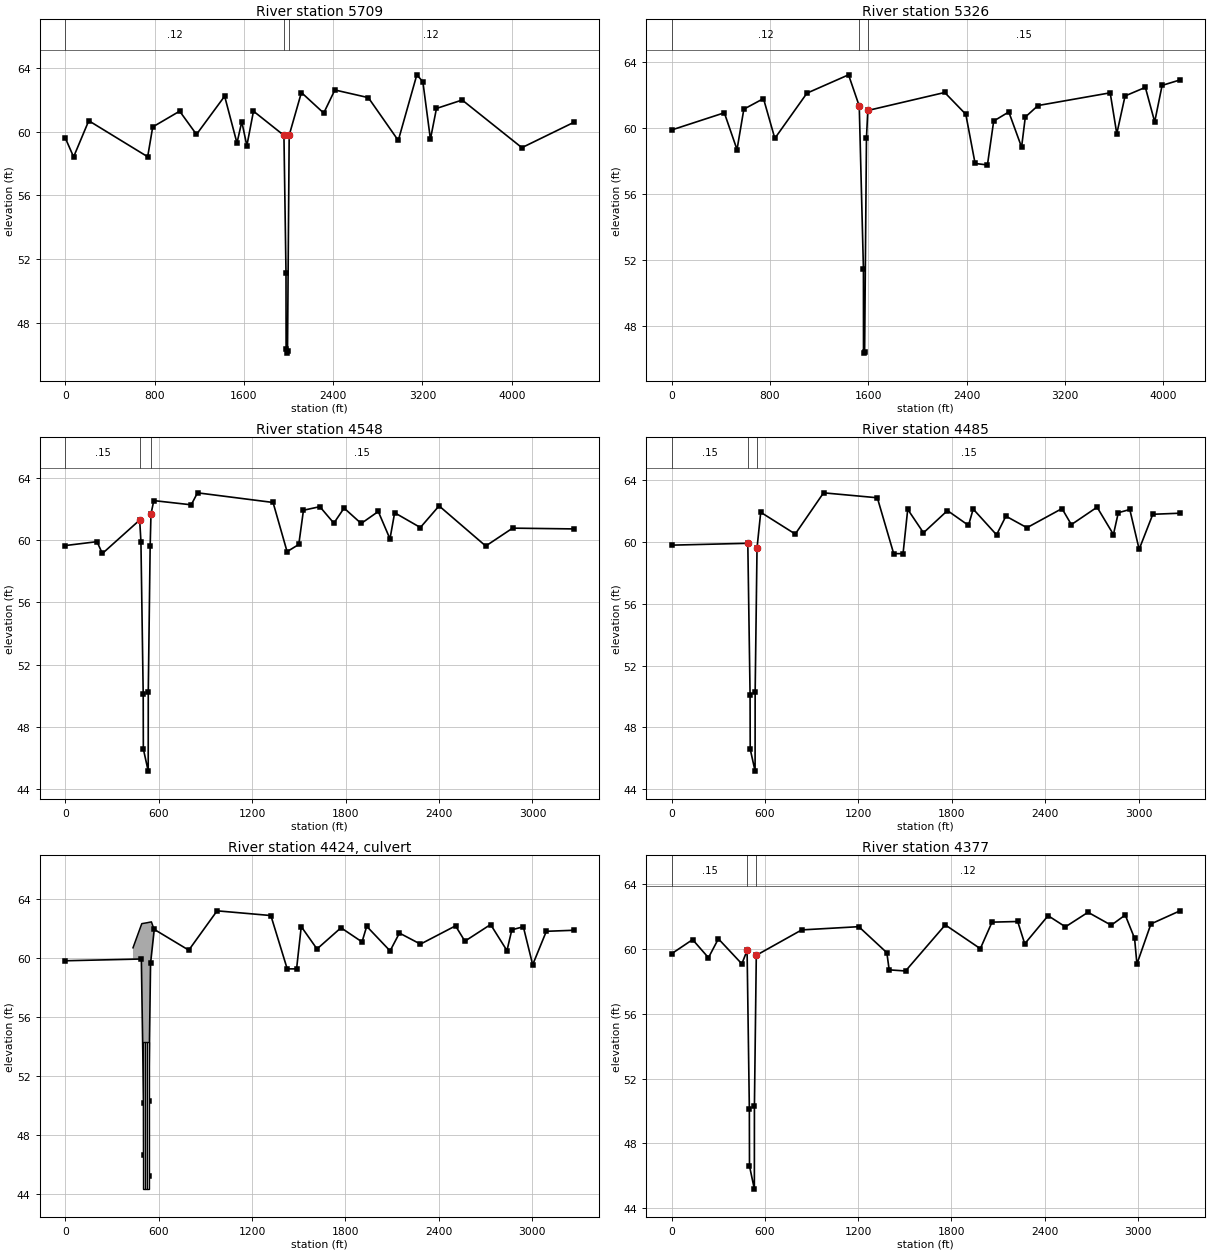
Type RM Length L Ch R = 1 ,5709    ,453.17,383.09,413.29
BEGIN DESCRIPTION:
             5733.311
END DESCRIPTION:
XS GIS Cut Line= 6
       3079252.4     13815905.68     3078018.107     13815779.73
     3077690.561     13815477.19     3077135.986     13815613.55
     3076187.703    13815187.656     3074969.429    13814966.878
#Sta/Elev= 30
       0   59.62   75.29   58.42  210.99   60.69  738.72   58.43  783.95    60.3
  1025.2   61.29 1175.98   59.83 1428.22   62.23 1538.75   59.29 1581.85   60.63
 1627.18   59.12 1686.59   61.29 1959.42   59.77 1977.88   51.13 1978.74   46.39
 1986.54   46.11 1991.37   46.27 2006.43   59.78 2115.86   62.46 2315.69   61.17
 2415.67   62.62 2715.24   62.14 2983.67   59.45 3149.79   63.57 3203.86   63.14
 3271.62   59.53 3325.72   61.46    3556   61.99 4090.91      59 4553.62   60.58
#Mann= 3 , 0 , 0
       0     .12       0 1959.42    .015       0 2006.43     .12       0
#XS Ineff= 2 , 0
       0 1902.23         2138.23       0
Permanent Ineff=
       T       T
Bank Sta=1959.42,2006.43
XS Rating Curve= 0
Exp/Cntr=.3,.1

Type RM Length L Ch R = 1 ,5326    ,841.12,778.8,765.47
BEGIN DESCRIPTION:
             5350.227
END DESCRIPTION:
XS GIS Cut Line= 6
     3079051.027    13815547.475     3077562.608    13815211.845
     3077492.782    13815213.091     3076225.587    13815048.749
     3075518.256    13814896.711     3074982.192    13814852.059
#Sta/Elev= 30
       0   59.88  428.24   60.92  531.55   58.69  587.07   61.14  746.82   61.78
  839.08   59.37 1100.48   62.11 1438.77   63.22 1525.79   61.33 1559.84   51.46
 1560.46   46.36 1569.39   46.41 1584.51   59.41 1595.63   61.06 2220.93   62.15
 2392.53   60.83 2468.16   57.85 2568.53   57.76 2619.41   60.42 2742.32   60.97
  2846.3   58.84 2876.59   60.66 2980.06   61.36 3567.01   62.13 3620.76   59.65
 3688.06   61.94 3853.09   62.46 3929.08   60.37 3989.34   62.58 4134.92   62.91
#Mann= 3 , 0 , 0
       0     .12       0 1525.79    .015       0 1595.63     .15       0
#XS Ineff= 2 , 0
       0 1451.01         1630.01       0
Permanent Ineff=
       T       T
Bank Sta=1525.79,1595.63
XS Rating Curve= 0
Exp/Cntr=.3,.1

Type RM Length L Ch R = 1 ,4548    ,70.15,62.89,69.32
BEGIN DESCRIPTION:
             4547.539
END DESCRIPTION:
XS GIS Cut Line= 4
     3078226.842    13814525.131     3077763.917     13814466.37
     3077672.569     13814454.46     3074969.981     13814339.09
#Sta/Elev= 30
       0   59.66  204.03   59.91  238.66   59.15  478.15    61.3  486.18   59.92
  500.76   50.12  501.62   46.59  532.97   45.16  533.34   50.27  545.42   59.62
  550.77   61.69  568.84   62.55  809.06   62.28  849.54   63.05 1334.54   62.43
 1424.62   59.27 1499.69   59.73 1529.71   61.93 1634.81   62.16 1724.89    61.1
 1790.53   62.07 1900.31   61.08 2010.15   61.85 2085.22   60.09 2115.25   61.77
  2280.4   60.82 2400.51   62.21 2700.15   59.63 2872.66   60.78 3263.81   60.73
#Mann= 3 , 0 , 0
       0     .15       0  478.15    .015       0  550.77     .15       0
#XS Ineff= 2 , 0
       0  408.25          575.25       0
Permanent Ineff=
       T       T
Bank Sta=478.15,550.77
XS Rating Curve= 0
Exp/Cntr=.5,.3

Type RM Length L Ch R = 1 ,4485    ,126.94,107.94,119.22
BEGIN DESCRIPTION:
             4484.648
END DESCRIPTION:
XS GIS Cut Line= 4
     3078228.339    13814462.673     3077762.784     13814403.21
     3077671.436      13814391.3     3074970.352    13814250.734
#Sta/Elev= 30
       0    59.8  489.18   59.92  503.76   50.12  504.62   46.59  535.97   45.16
  536.34   50.27  548.42   59.62  572.16   61.93  793.99   60.52  975.95   63.19
 1321.42   62.87 1426.56   59.25 1486.64   59.25 1516.69   62.12 1617.93    60.6
 1772.03   62.04 1907.21   61.08 1937.25   62.14 2087.46   60.47 2147.54   61.68
 2282.72   60.93 2508.02   62.17 2568.11   61.13 2733.33   62.26 2838.47   60.49
 2869.67    61.9 2943.61   62.11 3003.69   59.53  3091.5    61.8  3266.2   61.87
#Mann= 3 , 0 , 0
       0     .15       0  489.18    .015       0  548.42     .15       0
#XS Ineff= 2 , 0
       0  413.67          578.67       0
Permanent Ineff=
       T       T
Bank Sta=489.18,548.42
XS Rating Curve= 0
Exp/Cntr=.5,.3

Type RM Length L Ch R = 2 ,4424    ,,,
BEGIN DESCRIPTION:
Bissonet Culvert
END DESCRIPTION:
Bridge Culvert--1,0,-1,-1, 0
Deck Dist Width WeirC Skew NumUp NumDn MinLoCord MaxHiCord MaxSubmerge Is_Ogee
5,100,2.6,0, 5, 5, , , .95, 0, 0,0,,
  435.48  491.96  524.96  553.96  572.16
   60.68   62.32   62.38   62.44    61.9
       0       0       0       0       0
  406.49  487.96  520.96  549.96  587.36
   60.28   62.32   62.38   62.44   59.93
       0       0       0       0       0
BR Coef=-1 , 0 , 0 ,, 0 ,,,.8,-1,,0,
WSPro=,,,, 1 ,,,, 0 ,,,, 0 ,,,,-1 ,-1 ,-1 , 0 , 0 , 0 , 0 , 0
Multiple Barrel Culv=2,10,13,100,.013,.5,1,8,1,44.3,44.3, 3,Culvert #1  , 0 ,5
  506.46  502.46  519.96  515.96  533.46  529.46
Culvert Bottom n=.013
BC Design=,, 0 ,, 0 ,,,,,,

Type RM Length L Ch R = 1 ,4377    ,72.02,73.3,79.87
BEGIN DESCRIPTION:
              4376.71
END DESCRIPTION:
XS GIS Cut Line= 4
     3078231.108    13814347.125      3077757.94    13814294.431
     3077666.592    13814282.521     3074971.004    13814095.274
#Sta/Elev= 30
       0   59.72  134.72   60.59  236.63   59.47  300.45   60.64  451.38   59.09
  485.18   59.92  499.76   50.12  500.62   46.59  531.97   45.16  532.34   50.27
  544.42   59.62  836.52   61.19 1203.83   61.39 1384.27   59.78  1399.3   58.72
 1504.56   58.65 1760.17    61.5 1985.71   60.03  2060.9   61.67 2226.16   61.71
  2271.4   60.33 2421.76   62.07 2533.18   61.38  2678.6   62.28 2827.74   61.48
 2917.96   62.11  2978.1   60.67 2993.14   59.08 3083.35   61.56  3270.3   62.37
#Mann= 3 , 0 , 0
       0     .15       0  485.18    .015       0  544.42     .12       0
#XS Ineff= 2 , 0
       0  421.67          584.67       0
Permanent Ineff=
       T       T
Bank Sta=485.18,544.42
XS Rating Curve= 0
Exp/Cntr=.5,.3

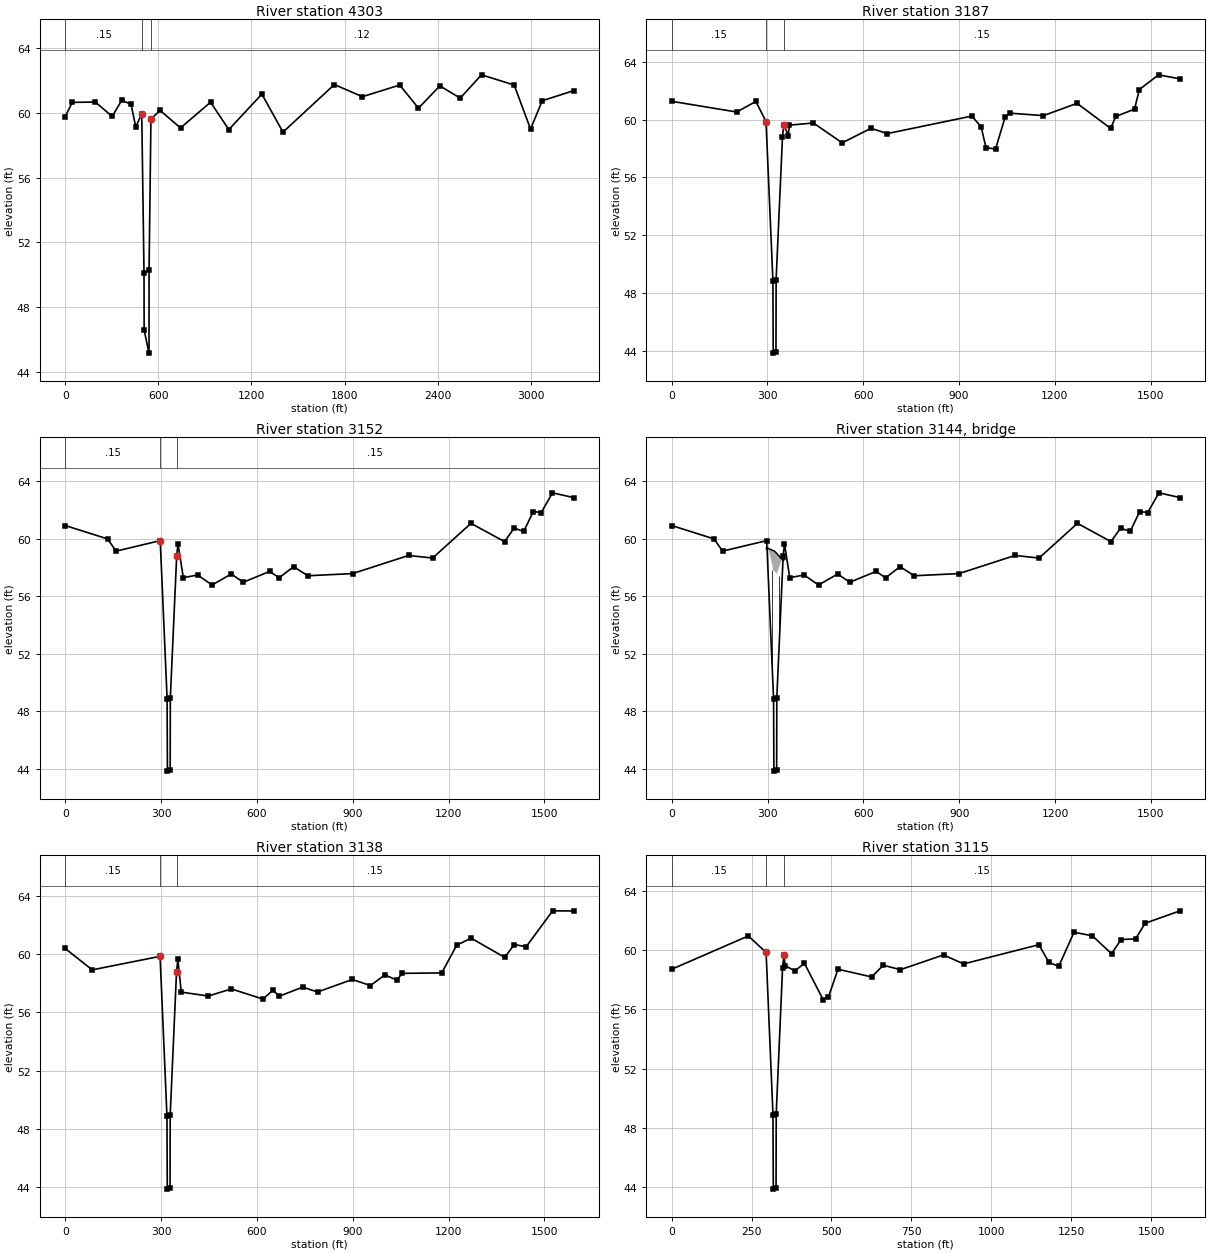
Type RM Length L Ch R = 1 ,4303    ,961.35,1115.94,938.09
BEGIN DESCRIPTION:
             4303.413
END DESCRIPTION:
XS GIS Cut Line= 4
     3078232.535    13814287.589     3077766.668     13814222.13
      3077675.32     13814210.22     3074971.446    13813989.946
#Sta/Elev= 30
       0   59.76   45.48   60.64   193.8   60.66  302.98   59.77  363.57   60.76
  424.16   60.53  454.46   59.13  493.18   59.92  507.76   50.12  508.62   46.59
  539.97   45.16  540.34   50.27  552.42   59.62  611.83   60.14   742.9   59.06
  936.62   60.65 1054.21   58.96 1267.21   61.15 1403.16    58.8 1734.25   61.74
 1914.85   60.99 2155.64   61.71 2276.04   60.28 2414.12   61.66 2545.19    60.9
 2682.38   62.34 2893.08   61.71 2998.43   58.99 3073.68   60.74  3275.4   61.36
#Mann= 3 , 0 , 0
       0     .15       0  493.18    .015       0  552.42     .12       0
#XS Ineff= 2 , 0
       0  436.67          597.67       0
Permanent Ineff=
       T       T
Bank Sta=493.18,552.42
XS Rating Curve= 0
Exp/Cntr=.3,.1

Type RM Length L Ch R = 1 ,3187    ,34.88,35,37.11
BEGIN DESCRIPTION:
             3187.476
END DESCRIPTION:
XS GIS Cut Line= 4
     3078255.666    13813322.316      3077975.39    13813304.462
     3077904.617     13813301.89     3076665.257    13813259.178
#Sta/Elev= 30
       0   61.26  203.58   60.52   263.7   61.25  295.45   59.86  316.99   48.87
  317.97   43.85   326.6   43.94  327.09   48.93  346.92   58.78  351.09   59.65
  364.85   58.89  368.79   59.61  443.84   59.76  533.89   58.39  623.94   59.39
  675.75   59.03     940   60.24  969.15   59.49  984.16   58.06 1014.17   57.96
 1044.19   60.17  1059.2   60.44 1164.26   60.27 1269.33   61.12 1374.39   59.39
  1390.8   60.21 1449.43   60.72 1464.44   62.07 1524.48   63.09 1591.76   62.81
#Mann= 3 , 0 , 0
       0     .15       0  295.45    .015       0  351.09     .15       0
#XS Ineff= 2 , 0
       0   239.6           531.6       0
Permanent Ineff=
       T       T
Bank Sta=295.45,351.09
XS Rating Curve= 0
Exp/Cntr=.5,.3

Type RM Length L Ch R = 1 ,3152    ,13.99,14,14.84
BEGIN DESCRIPTION:
             3152.476
END DESCRIPTION:
XS GIS Cut Line= 4
     3078256.487    13813288.083     3077975.993    13813269.462
      3077905.22     13813266.89     3076666.603    13813224.204
#Sta/Elev= 30
       0   60.91  132.47   59.98  159.34   59.13  297.45   59.86  318.99   48.87
  319.97   43.85   328.6   43.94  329.09   48.93  348.92   58.78  353.09   59.65
  369.66   57.29  414.69   57.47  459.72   56.78  519.75   57.54  557.46   56.97
  639.82   57.72  669.84   57.28  714.87   58.05  759.54   57.42  899.44   57.57
 1075.08   58.83 1150.12   58.65  1270.2   61.06 1375.26   59.79 1405.28   60.73
 1435.29    60.5 1465.31   61.88 1490.14   61.81 1525.35   63.18 1591.28   62.85
#Mann= 3 , 0 , 0
       0     .15       0  297.45    .015       0  348.92     .15       0
#XS Ineff= 2 , 0
       0  236.04          525.04       0
Permanent Ineff=
       T       T
Bank Sta=297.45,348.92
XS Rating Curve= 0
Exp/Cntr=.5,.3

Type RM Length L Ch R = 3 ,3144    ,,,
BEGIN DESCRIPTION:
Grape Pedestrian Brige
END DESCRIPTION:
Bridge Culvert--1,0,-1,-1, 0
Deck Dist Width WeirC Skew NumUp NumDn MinLoCord MaxHiCord MaxSubmerge Is_Ogee
5,4,2.6,0, 5, 5, , , .95, 0, 0,0,,
 296.408 296.418 321.918 349.418 355.838
   59.31   59.37   59.13   58.48   58.61
       0   57.97   57.73   57.08       0
 296.408 296.418 321.918 349.418 355.838
   59.31   59.37   59.13   58.48   58.61
       0   57.97   57.73   57.08       0
Pier Skew, UpSta & Num, DnSta & Num=  ,314.92, 2 ,314.92, 2 , 0 , 0 , 0 ,,
       1       1
       0     100
       1       1
       0     100
Pier Skew, UpSta & Num, DnSta & Num=  ,336.92, 2 ,336.92, 2 , 0 , 0 , 0 ,,
       1       1
       0     100
       1       1
       0     100
BR Coef=-1 , 1 , 1 ,1.25, 0 ,,,.8,-1,2,0,
WSPro=,,,, 1 ,,,, 0 ,,,, 0 ,,,,-1 ,-1 ,-1 , 0 , 0 , 0 , 0 , 0
BC Design=,, 0 ,, 0 ,,,,,,

Type RM Length L Ch R = 1 ,3138    ,25.08,23.38,28.94
BEGIN DESCRIPTION:
             3138.476
END DESCRIPTION:
XS GIS Cut Line= 4
     3078256.822    13813274.099     3077976.234    13813255.462
     3077905.461     13813252.89     3076667.142    13813210.215
#Sta/Elev= 30
       0    60.4   84.51   58.93  296.95   59.86  318.49   48.87  319.47   43.85
   328.1   43.94  328.59   48.93  348.42   58.78  352.59   59.65  363.35    57.4
  447.96   57.13  520.09   57.62  618.95   56.92  650.04   57.53  670.18   57.12
  743.31   57.74  789.94   57.41  898.75   58.27  955.34   57.85 1000.37   58.58
 1038.65   58.22  1054.2   58.69 1178.55   58.72 1225.51   60.63 1270.53   61.11
 1375.59   59.79 1405.61   60.67 1442.81   60.52 1525.68   62.99 1591.08   62.98
#Mann= 3 , 0 , 0
       0     .15       0  296.95    .015       0  348.42     .15       0
#XS Ineff= 2 , 0
       0  234.85          522.85       0
Permanent Ineff=
       T       T
Bank Sta=296.95,348.42
XS Rating Curve= 0
Exp/Cntr=.5,.3

Type RM Length L Ch R = 1 ,3115    ,1219.1,1227.01,1235.6
BEGIN DESCRIPTION:
             3115.095
END DESCRIPTION:
XS GIS Cut Line= 4
     3078257.681    13813238.234      3077977.48    13813232.113
     3077906.708    13813229.541     3076668.488     13813175.24
#Sta/Elev= 30
       0   58.72  239.74   60.97  295.45   59.86  316.99   48.87  317.97   43.85
   326.6   43.94  327.09   48.93  346.92   58.78  351.09   59.65   355.3   58.96
  385.33   58.61  415.36   59.12  473.75   56.67  490.43   56.84  520.46   58.72
  625.56    58.2  662.18   58.99  715.64   58.69  850.62   59.69  913.43   59.08
 1148.98   60.38 1180.38   59.18 1211.12   58.92  1258.9   61.22 1316.22   60.98
 1376.28   59.77 1406.31   60.73 1451.35   60.77 1481.38   61.83  1590.5   62.67
#Mann= 3 , 0 , 0
       0     .15       0  295.45    .015       0  351.09     .15       0
#XS Ineff= 2 , 0
       0   225.6           520.6       0
Permanent Ineff=
       T       T
Bank Sta=295.45,351.09
XS Rating Curve= 0
Exp/Cntr=.3,.1