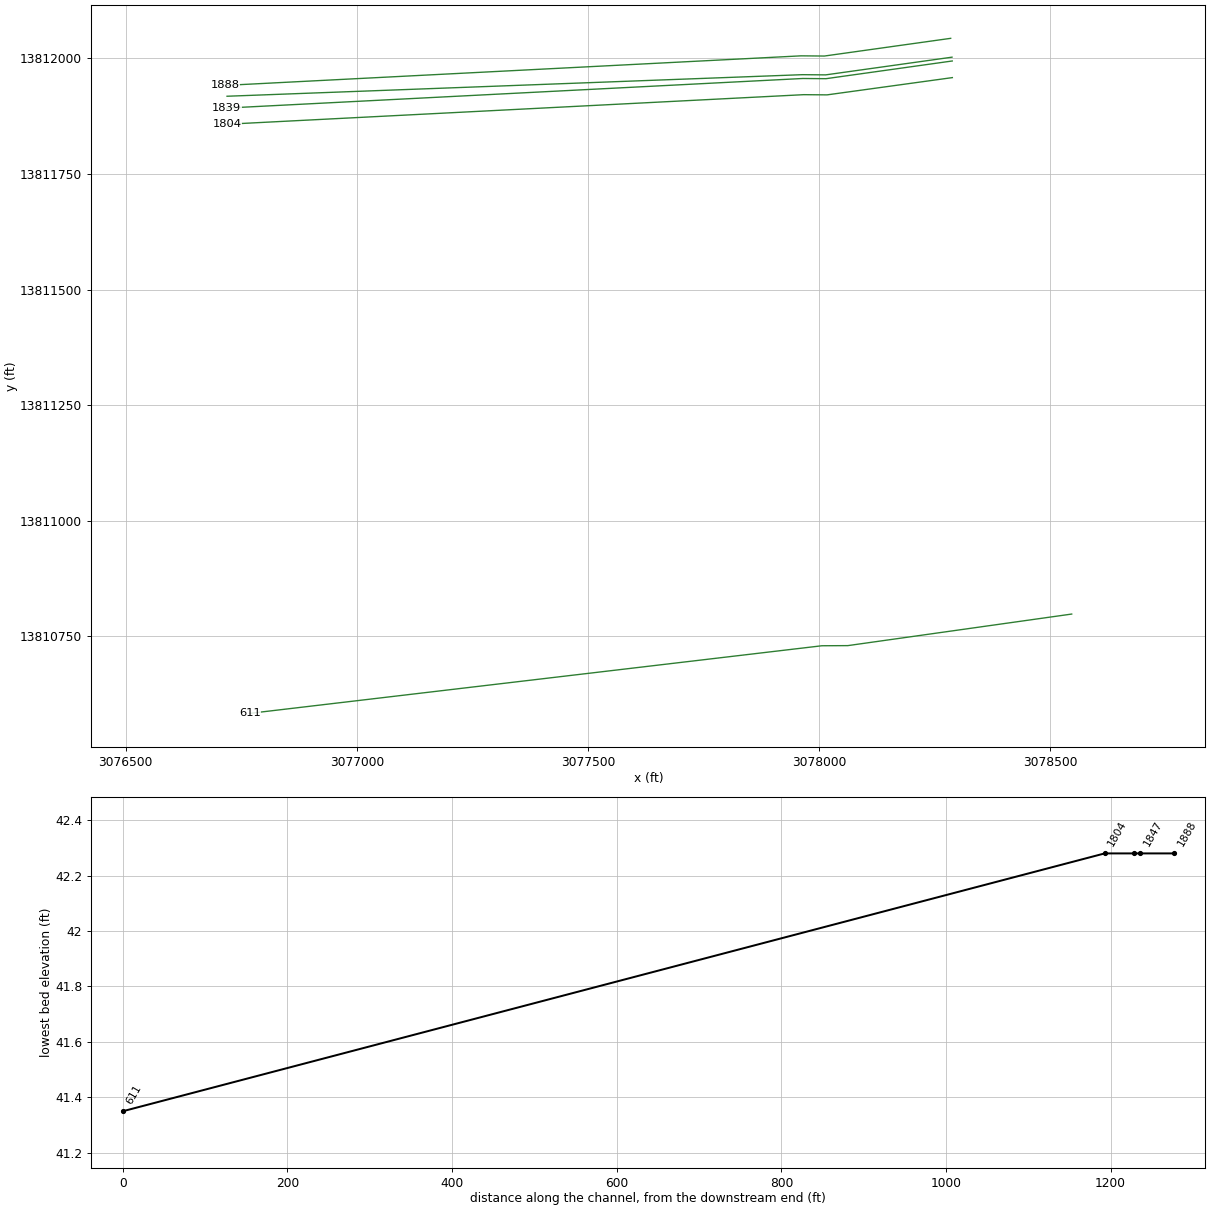
HEC-RAS study D133-00-00.prj: D133-00-00

--- D133-00-00.g01 (geometry) --- (continued)

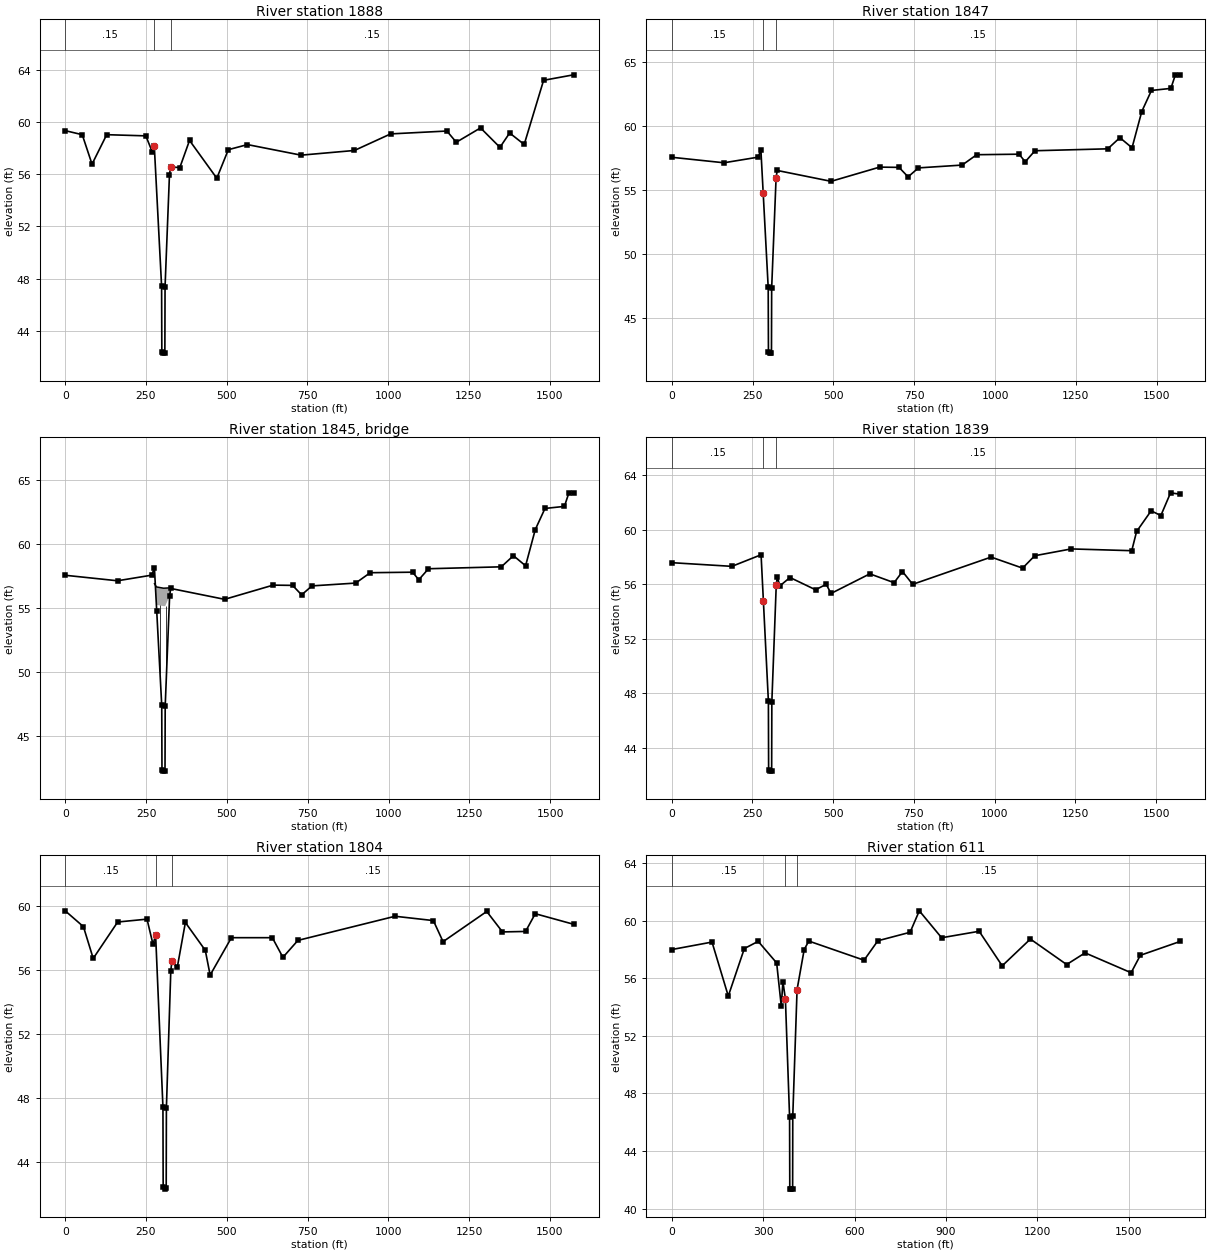
Type RM Length L Ch R = 1 ,1888    ,40.86,40.78,36.65
BEGIN DESCRIPTION:
             1888.091
END DESCRIPTION:
XS GIS Cut Line= 4
     3078284.737    13812043.354     3078011.547     13812005.06
     3077961.124    13812005.488     3076714.904    13811941.508
#Sta/Elev= 30
       0   59.34   52.75   59.03   83.04   56.77  128.48   59.03  249.65   58.94
  269.35   57.73  275.86   58.17   298.5   47.41  299.22   42.39  303.55   42.28
   308.6   42.32  309.19   47.36  322.84   55.95  326.29   56.55  354.95   56.51
  384.99   58.59  469.45   55.69  505.14   57.88  564.45   58.27  730.44   57.46
  895.66   57.82 1007.76   59.09 1181.92   59.31 1211.07   58.45 1286.17   59.55
 1346.25   58.06 1376.29   59.16 1421.35   58.28 1481.43    63.2 1574.15   63.62
#Mann= 3 , 0 , 0
       0     .15       0  275.86    .015       0  326.29     .15       0
#XS Ineff= 2 , 0
       0  181.23          486.23       0
Permanent Ineff=
       T       T
Bank Sta=275.86,326.29
XS Rating Curve= 0
Exp/Cntr=.5,.3

Type RM Length L Ch R = 1 ,1847    ,8.26,8.26,12.46
BEGIN DESCRIPTION:
             1847.307
END DESCRIPTION:
XS GIS Cut Line= 4
     3078287.648    13812002.603     3078014.458    13811964.309
     3077964.035    13811964.737     3076719.304    13811918.075
#Sta/Elev= 30
       0   57.58  161.71   57.15  267.74   57.59  275.86   58.17  282.98   54.79
   298.5   47.41  299.22   42.39  303.55   42.28   308.6   42.32  309.19   47.36
  322.84   55.95  326.29   56.55  492.94    55.7  643.04   56.81  703.09   56.79
  731.03   56.05  763.13   56.75  898.22   56.97  943.25   57.78 1074.12   57.82
 1093.36   57.23 1123.38   58.09 1348.54   58.24 1386.03   59.11 1423.59   58.32
 1453.61   61.15 1483.63    62.8 1543.68   62.96 1557.57   64.02 1571.89   63.99
#Mann= 3 , 0 , 0
       0     .15       0  282.98    .015       0  322.84     .15       0
#XS Ineff= 2 , 0
       0  170.72          476.72       0
Permanent Ineff=
       T       T
Bank Sta=282.98,322.84
XS Rating Curve= 0
Exp/Cntr=.5,.3

Type RM Length L Ch R = 3 ,1845    ,,,
BEGIN DESCRIPTION:
Birdwood Pedestrian Bridge
END DESCRIPTION:
Bridge Culvert--1,0,-1,-1, 0
Deck Dist Width WeirC Skew NumUp NumDn MinLoCord MaxHiCord MaxSubmerge Is_Ogee
3,5,2.6,0, 4, 4, , , .95, 0, 0,0,,
  276.14  282.09  304.09  326.27
   56.92   56.67   56.57    56.6
       0   55.27   55.17   55.17
  277.14  283.09  305.09   327.3
   56.92   56.67   56.57    56.6
       0   55.27   55.17   55.17
Pier Skew, UpSta & Num, DnSta & Num=  ,293.09, 2 ,294.09, 2 , 0 , 0 , 0 ,,
       1       1
       0     100
       1       1
       0     100
Pier Skew, UpSta & Num, DnSta & Num=  ,312.09, 2 ,313.09, 2 , 0 , 0 , 0 ,,
       1       1
       0     100
       1       1
       0     100
BR Coef=-1 , 1 , 1 ,1.25, 0 ,,,.8,-1,2,0,
WSPro=,,,, 1 ,,,, 0 ,,,, 0 ,,,,-1 ,-1 ,-1 , 0 , 0 , 0 , 0 , 0
BC Design=,, 0 ,, 0 ,,,,,,

Type RM Length L Ch R = 1 ,1839    ,35.69,35.03,35.05
BEGIN DESCRIPTION:
              1839.05
END DESCRIPTION:
XS GIS Cut Line= 4
     3078288.121    13811994.354     3078014.931     13811956.06
     3077964.508    13811956.488     3076718.288    13811892.508
#Sta/Elev= 30
       0   57.59  186.46   57.32  276.86   58.17  283.98   54.79   299.5   47.41
  300.22   42.39  304.55   42.28   309.6   42.32  310.19   47.36  323.84   55.95
  327.29   56.55  334.75   55.88  366.42    56.5  445.58    55.6  478.49      56
  493.51   55.33  613.67   56.77  688.77   56.12  714.73   56.94   746.4      56
  989.17      58  1086.7   57.19 1124.34    58.1 1237.21    58.6 1424.74   58.47
 1439.76   59.88 1484.82    61.4 1514.86   61.05  1544.9   62.72 1574.15   62.62
#Mann= 3 , 0 , 0
       0     .15       0  283.98    .015       0  323.84     .15       0
#XS Ineff= 2 , 0
       0  184.17          490.17       0
Permanent Ineff=
       T       T
Bank Sta=283.98,323.84
XS Rating Curve= 0
Exp/Cntr=.5,.3

Type RM Length L Ch R = 1 ,1804    ,1187.56,1192.79,1210.14
BEGIN DESCRIPTION:
             1804.022
END DESCRIPTION:
XS GIS Cut Line= 4
     3078288.351      13811958.4     3078017.349     13811921.06
     3077966.926    13811921.488     3076719.206    13811857.537
#Sta/Elev= 30
       0   59.69   56.38    58.7   86.66   56.71  162.37   58.99  253.22   59.17
  271.74   57.59  279.86   58.17   302.5   47.41  303.22   42.39  307.55   42.28
   312.6   42.32  313.19   47.36  326.84   55.95  330.29   56.55  346.83   56.15
  371.94   58.96  433.56   57.22  448.58   55.67  514.42   58.01  641.07   58.01
  673.87   56.78  720.23   57.84 1021.02   59.35 1139.48   59.08 1169.52   57.76
  1304.7   59.65 1353.47   58.37 1424.86    58.4  1454.9   59.51 1573.35   58.85
#Mann= 3 , 0 , 0
       0     .15       0  279.86    .015       0  330.29     .15       0
#XS Ineff= 2 , 0
       0  192.23          498.23       0
Permanent Ineff=
       T       T
Bank Sta=279.86,330.29
XS Rating Curve= 0
Exp/Cntr=.3,.1

Type RM Length L Ch R = 1 ,611     ,174.23,611.24,227.84
BEGIN DESCRIPTION:
              611.235
END DESCRIPTION:
XS GIS Cut Line= 4
     3078546.571    13810797.919     3078062.214    13810729.636
     3078006.376    13810729.353     3076768.261    13810583.063
#Sta/Elev= 30
       0   57.99  132.32   58.51  185.69   54.76  238.36   58.06   283.8   58.56
  344.37   57.06  359.54   54.06  364.88   55.77  373.08   54.55  386.77   46.37
  387.42   41.37  391.82   41.35  396.77   41.38  397.23   46.41  411.34   55.21
  434.69   57.99   449.8   58.58  631.05   57.25  676.36    58.6  782.09   59.19
   812.3   60.68  885.49   58.81 1008.66   59.26 1084.18   56.86 1176.67   58.72
 1295.64   56.95 1356.06   57.76  1507.1   56.38 1537.31   57.59 1667.45   58.55
#Mann= 3 , 0 , 0
       0     .15       0  373.08    .015       0  411.34     .15       0
#XS Ineff= 2 , 0
       0  268.28          584.28       0
Permanent Ineff=
       T       T
Bank Sta=373.08,411.34
XS Rating Curve= 0
Exp/Cntr=.3,.1

Chan Stop Cuts=-1